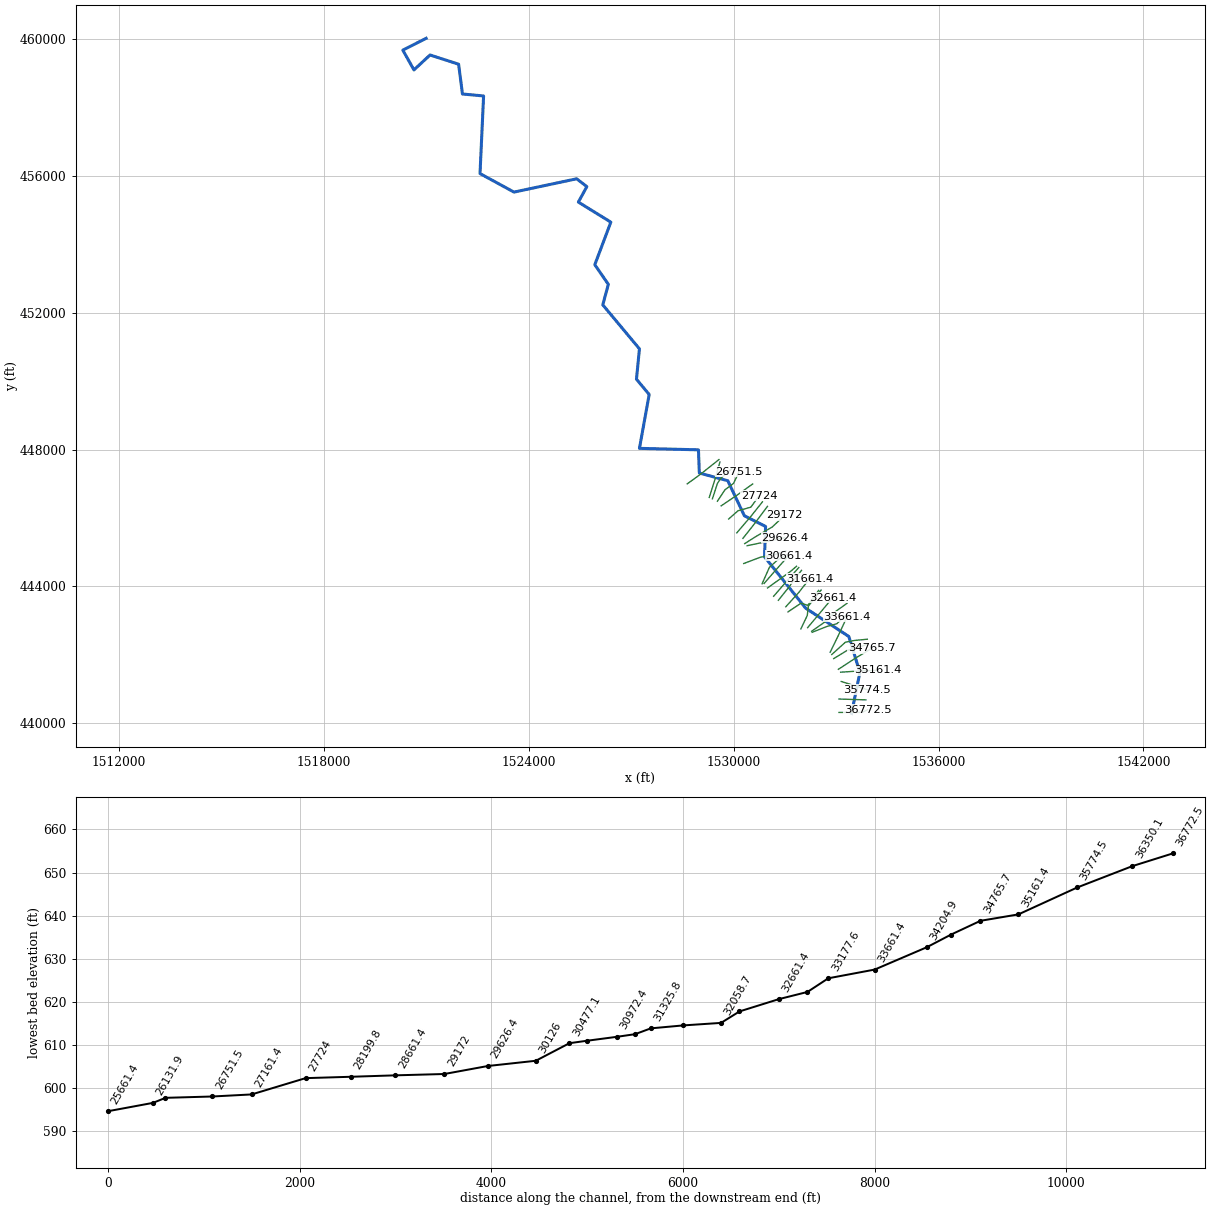
--- GRAGSTNCR.prj (project) ---

Proj Title=GRAGSTNCR
Current Plan=p01
Default Exp/Contr=0,0
English Units
Geom File=g01
Flow File=f01
Plan File=p01
BEGIN DESCRIPTION:
END DESCRIPTION:
DSS Export Rating Curves= 0
DSS Export Rating Curve Sorted= 0
DSS Export Volume Flow Curves= 0
DXF OffsetX= 0
DXF OffsetY= 0
DXF ScaleX= 0
DXF ScaleY= 0

--- GRAGSTNCR.p01 (plan) ---

Plan Title=Floodplain
Program Version=4.00
Geom File=g01
Flow File=f01
K Sum by GR=0
Std Step Tol=0.01
Critical Tol=0.01
Num of Std Step Trials=20
Max Error Tol=0.3
Flow Tol Ratio=0.001
Split Flow NTrial=30
Split Flow Tol=0.02
Split Flow Ratio=0.02
Log Output Level=0
Friction Slope Method=1
Unsteady Friction Slope Method=2
Unsteady Bridges Friction Slope Method=1
Global Log Level=0
CheckData=False
Run HTab=0
Run UNet=0
Run PostProcess=0
UNET Theta=0
UNET Theta Warmup=0
UNET ZTol=0
UNET ZSATol=0
UNET MxIter=0
UNET MaxInSteps=0
UNET DtIC=0
UNET DtMin=0
UNET MaxCRTS=0
UNET WFStab=0
UNET SFStab=0
UNET WFX=0
UNET SFX=0
UNET DSS MLevel=0
UNET DZMax Abort=0
UNET Convert EG Bridges=0
UNET Use Existing IB Tables=0
UNET Froude Limit=0
UNET Froude Power=0
Write IC File=0
Echo Input=False
Echo Output=False
Write Detailed=0

--- GRAGSTNCR.f01 (steady flow) ---

Flow Title=NFF Regression Equation
Program Version=4.00
Number of Profiles= 1
Profile Names=P100yr
River Rch & RM=GRAGSTNCR,Main            ,36772.5
     376
River Rch & RM=GRAGSTNCR,Main            ,34459.2
     381
River Rch & RM=GRAGSTNCR,Main            ,32960.3
     422
River Rch & RM=GRAGSTNCR,Main            ,32661.4
     543
River Rch & RM=GRAGSTNCR,Main            ,22481.5
    1326
River Rch & RM=GRAGSTNCR,Main            ,18871.7
    1434
River Rch & RM=GRAGSTNCR,Main            ,18583.2
    1509
River Rch & RM=GRAGSTNCR,Main            ,14383.3
    1675
River Rch & RM=GRAGSTNCR,Main            ,9885.3
    1771
Boundary for River Rch & Prof#=GRAGSTNCR,Main            , 1
Up Type= 0
Dn Type= 3
Dn Slope=0.0007
DSS Import GetInterval= 0
DSS Import GetPeak= 0
DSS Import FillOption= 0

--- GRAGSTNCR.g01 (geometry) ---

Geom Title=USGS 10m DEM
Program Version=4.00

River Reach=GRAGSTNCR       ,Main
Reach XY= 30
     1533454.218      440280.591      1533698.14      441477.487
     1533374.386      442529.651      1532108.95      443360.045
      1530905.68      444861.248     1530936.747      445749.184
     1530315.084      446062.965     1529829.439      447088.537
     1528996.297      447313.339     1528970.948      447992.243
     1527242.863      448035.361     1527528.005      449611.492
      1527155.51      450058.471     1527242.489      450947.433
     1526169.086      452233.575     1526331.639      452834.877
     1525935.412      453408.712     1526405.392       454654.15
     1525454.011      455240.577     1525702.356      455693.492
     1525405.478      455923.416     1523569.212      455533.513
     1522574.171      456075.046     1522678.813      458346.268
     1522059.942      458404.265     1521947.408      459275.622
     1521110.451      459544.947     1520639.336       459109.07
     1520313.452      459687.366     1520996.173      460032.675

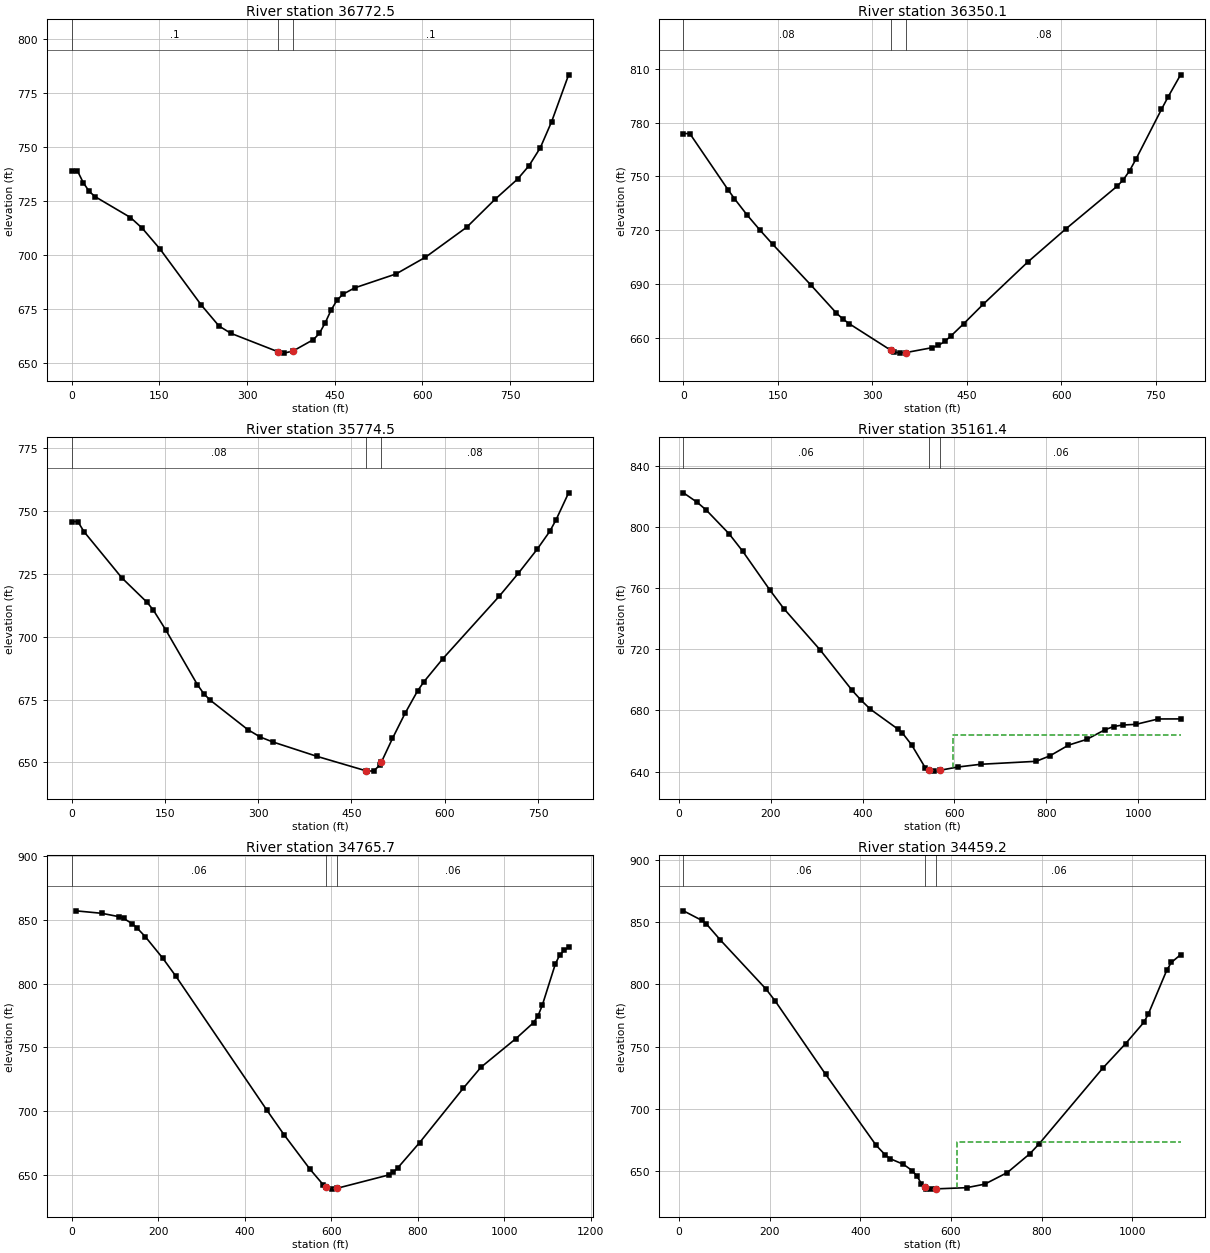
Type RM Length L Ch R = 1 ,36772.5 ,424.1,422.4,420.8
XS GIS Cut Line= 3
     1533088.492      440308.388     1533764.186      440308.388
     1533920.947      440384.065
#Sta/Elev= 30
       0  738.86    10.1  738.86    20.2  733.32    30.3  729.32    40.3  726.91
   100.8  717.25     121  712.26   151.3  702.65   221.9  676.69   252.1  667.01
   272.3  663.64   353.5  655.03   363.1  654.45   378.5   655.4   413.5  660.71
   423.6  663.56   433.7  668.49   443.7  674.37   453.8  678.94   463.9  681.72
   484.1  684.67   554.7  691.11   605.1  698.87   675.7  712.78     724  725.67
   762.7  735.08   782.1  741.23   801.4  749.55   820.8  761.67   849.8  783.32
#Mann= 3 , 0 , 0
       0      .1       0   353.5    .045       0   378.5      .1       0
Bank Sta=353.5,378.5
XS Rating Curve= 0 ,0
Exp/Cntr=0.3,0.1

Type RM Length L Ch R = 1 ,36350.1 ,580.7,575.6,569.2
XS GIS Cut Line= 2
     1533085.789       440700.29        1533875.      440675.965
#Sta/Elev= 30
       0   773.9    10.1   773.9    70.9  742.55      81  737.59   101.2  728.47
   121.5  720.09   141.7  712.19   202.5  689.43   242.9  673.84   253.1  670.56
   263.2  667.92   328.9  653.21   334.1   652.2   344.2   651.5   353.9  651.84
   394.8  654.53   404.9  655.78     415  658.04   425.2  661.17   445.4  667.99
   475.8  678.63   546.6   702.2   607.4  720.76   688.4  744.43   698.5  748.04
   708.6  753.18   718.7   759.6   759.2  787.34   769.3  794.03   789.6  806.65
#Mann= 3 , 0 , 0
       0     .08       0   328.9    .045       0   353.9     .08       0
Bank Sta=328.9,353.9
XS Rating Curve= 0 ,0
Exp/Cntr=0.3,0.1

Type RM Length L Ch R = 1 ,35774.5 ,586.1,613.1,636.6
XS GIS Cut Line= 2
     1533153.358      441213.818     1533915.541      440973.271
#Sta/Elev= 30
       0  745.73    10.1  745.73    20.2  741.67    80.9  723.36   121.4  713.64
   131.5  710.57   151.8  702.54   202.3  680.93   212.5  677.36   222.6  674.82
   283.3  663.06   303.5  660.08   323.7  658.13   394.6  652.41   473.2  646.69
   475.5  646.54   485.6  646.61   495.7   648.9   498.2  650.14     516  659.53
   536.2   669.5   556.4  678.44   566.6  682.08   596.9   691.2     688  716.15
   718.3  725.15   748.7  734.75   768.9  741.84     779  746.43   799.2  757.15
#Mann= 3 , 0 , 0
       0     .08       0   473.2    .045       0   498.2     .08       0
Bank Sta=473.2,498.2
XS Rating Curve= 0 ,0
Exp/Cntr=0.3,0.1

Type RM Length L Ch R = 1 ,35161.4 ,381.9,395.7,409.6
XS GIS Cut Line= 5
     1533134.123      441485.345      1533470.91      441507.938
     1533679.216      441521.912     1534011.111      441533.878
     1534224.805      441541.583
#Sta/Elev= 30
     9.9  822.22    39.7  816.04    59.6  810.94   109.2  795.45     139     784
   198.6  758.45   228.3  746.58   307.8  719.42   377.3  693.05   397.2  686.49
   417.1  680.72   476.7  667.81   486.7  665.19   506.6  657.51   536.4  642.51
   543.9  640.98   556.4   640.3   568.9  640.88   606.7  642.96     657  644.78
   777.8  646.71     808  650.31   848.2  657.28   888.1  661.06     927  667.24
   946.5  669.45   965.9  670.42   995.1  670.88  1043.7   674.4  1092.3  674.43
#Mann= 3 , 0 , 0
     9.9     .06       0   543.9    .045       0   568.9     .06       0
#XS Ineff= 2 , 0
                          595.76          664.12
Permanent Ineff=
       F       F
Bank Sta=543.9,568.9
XS Rating Curve= 0 ,0
Exp/Cntr=0.3,0.1

Type RM Length L Ch R = 1 ,34765.7 ,314.8,306.5,298.8
XS GIS Cut Line= 3
     1533068.318      441570.463     1533563.607      441893.782
      1534041.24      442181.085
#Sta/Elev= 30
      10  857.21    70.2  855.25   110.3  852.58   120.3  851.31   140.4  847.06
   150.4  844.12   170.4  836.96   210.5  820.21   240.6  806.17   451.1  700.99
   491.2   681.5   551.4  654.33   581.5  642.34   589.1  640.26   601.6  638.81
   614.1   639.5   733.4  649.95   743.5  651.96   753.6  655.33   804.3  675.23
   905.6  718.07   946.2  734.43  1027.3     757  1067.8  769.45  1077.9  774.57
  1088.1  783.16  1118.5  815.79  1128.6  822.66  1138.7  826.16  1148.9  828.73
#Mann= 3 , 0 , 0
       0     .06       0   589.1    .045       0   614.1     .06       0
Bank Sta=589.1,614.1
XS Rating Curve= 0 ,0
Exp/Cntr=0.3,0.1

Type RM Length L Ch R = 1 ,34459.2 ,252.7,254.2,254.3
XS GIS Cut Line= 4
     1532930.894      441883.221     1533319.472       442120.16
     1533693.835      442224.413      1533940.25      442314.449
#Sta/Elev= 30
    10.1  859.02    50.6  851.35    60.7  848.49      91  835.77   192.2  796.18
   212.4  786.62   323.6  727.74   434.9   670.8   455.1  663.05   465.1  660.16
     495  655.53   514.9  650.37   524.9  646.06   534.8  639.98   542.3  636.99
   544.8  635.99   554.8  635.62   567.3  635.83   634.5  636.78   674.3  639.61
   724.2  648.93     774  664.09   793.9   671.8   934.5  732.69     985  752.45
  1025.4   769.6  1035.4  776.48  1075.8  811.45  1085.9  817.61  1106.1  823.77
#Mann= 3 , 0 , 0
    10.1     .06       0   542.3    .045       0   567.3     .06       0
#XS Ineff= 2 , 0
                          612.54          673.47
Permanent Ineff=
       F       F
Bank Sta=542.3,567.3
XS Rating Curve= 0 ,0
Exp/Cntr=0.3,0.1

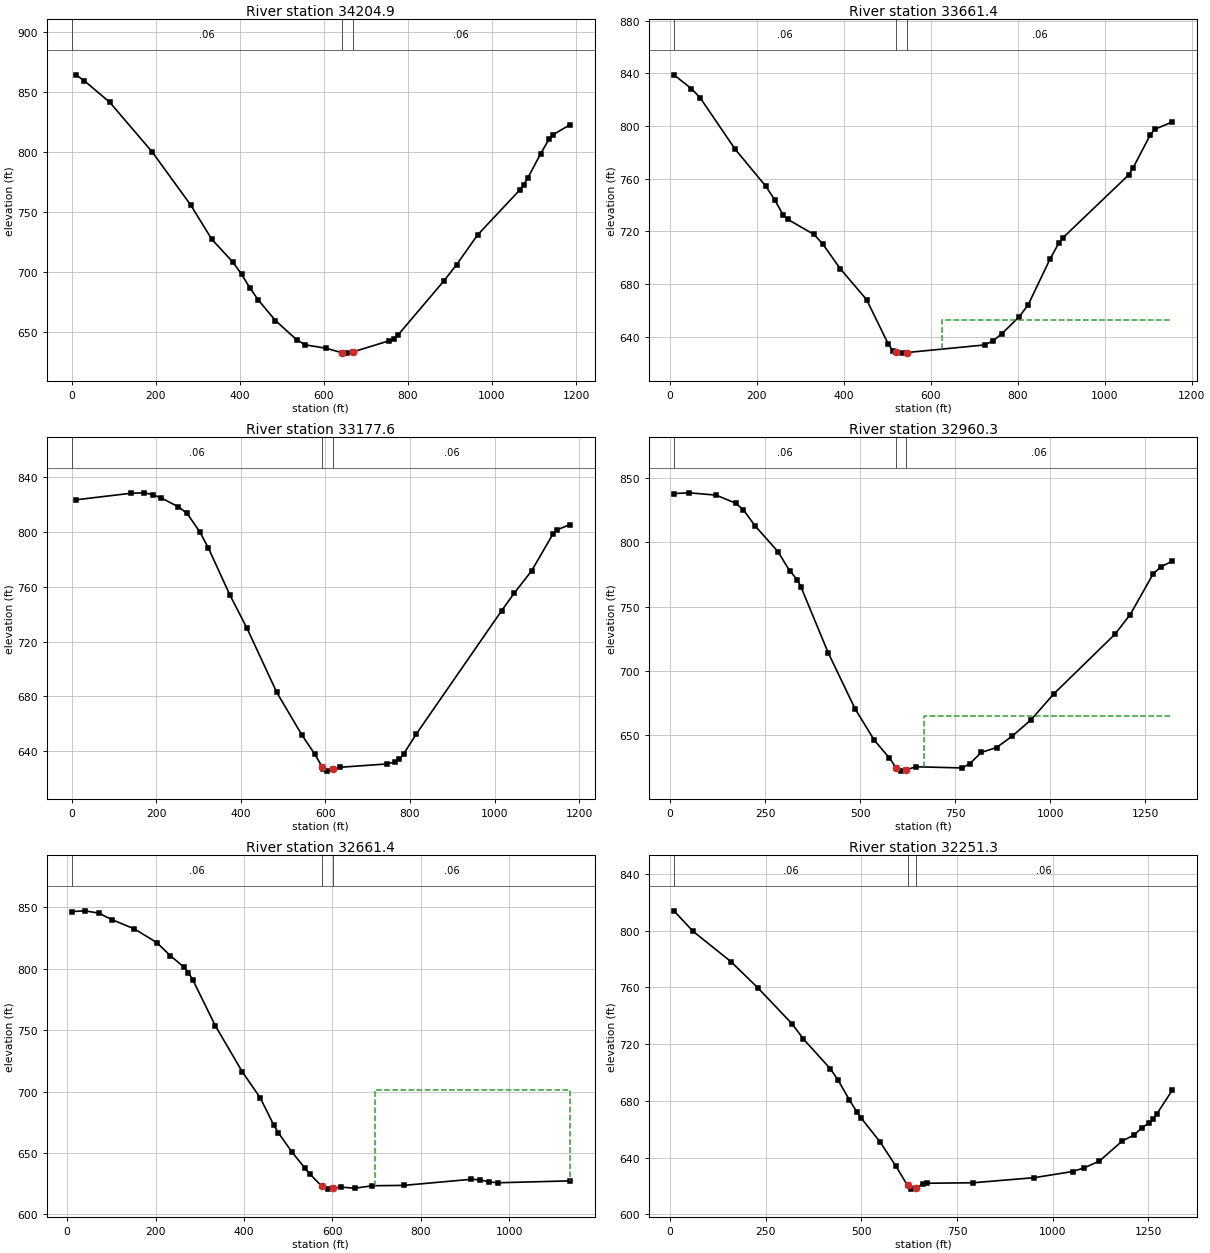
Type RM Length L Ch R = 1 ,34204.9 ,516.9,543.5,566.9
XS GIS Cut Line= 4
     1532874.761      442002.751     1533272.085      442361.837
     1533537.455      442413.963     1533915.031      442450.282
#Sta/Elev= 30
    10.1  864.57    30.3  859.62    90.9  841.65     192   800.2   282.9  756.31
   333.5  727.53     384  708.38   404.2  698.45   424.4   686.9   444.6  676.71
     485   659.8   535.5  643.77   555.6  639.57   605.7  636.72   643.2  632.95
   655.7  632.67   668.2  633.56   755.9  643.03   765.9  644.59   775.9  647.54
   885.8  692.94   915.8  706.39   965.7  731.14  1065.5  768.41  1075.5  772.98
  1085.5  778.84  1115.4  798.63  1135.4  810.79  1145.4  814.74  1185.3  822.92
#Mann= 3 , 0 , 0
       0     .06       0   643.2    .045       0   668.2     .06       0
Bank Sta=643.2,668.2
XS Rating Curve= 0 ,0
Exp/Cntr=0.3,0.1

Type RM Length L Ch R = 1 ,33661.4 ,497.4,483.8,448.5
XS GIS Cut Line= 3
     1532826.641      442068.033     1533061.051      442547.055
     1533324.211      443110.562
#Sta/Elev= 30
    10.1  838.79    50.3  828.31    70.4  821.35   150.9  782.27   221.4  754.15
   241.5  744.04   261.6  732.06   271.7  729.04   332.1  717.58   352.2  710.34
   392.4  691.56   452.8  668.16   503.1  634.12   513.2  629.25   520.8  628.09
   533.3  627.49   545.8  627.94   723.9   633.7     744  636.91     764  642.31
   804.1  655.28   824.2  664.21   874.4  698.91   894.4  710.92   904.5  715.21
  1054.9  762.73  1064.9  767.91  1105.1  793.39  1115.1  797.45  1155.2  802.97
#Mann= 3 , 0 , 0
    10.1     .06       0   520.8    .045       0   545.8     .06       0
#XS Ineff= 2 , 0
                          625.32          652.76
Permanent Ineff=
       F       F
Bank Sta=520.8,545.8
XS Rating Curve= 0 ,0
Exp/Cntr=0.3,0.1

Type RM Length L Ch R = 1 ,33177.6 ,202.3,217.3,232.2
XS GIS Cut Line= 4
     1532299.064      442653.222     1532741.343      442826.236
      1533020.93      442902.056     1533321.639      443185.448
#Sta/Elev= 30
    10.1  823.54   141.5  828.38   171.8  828.65     192  827.33   212.2  824.84
   252.6  818.43   272.8  813.71   303.1  800.12   323.3  788.41   373.9   754.2
   414.3     730   484.9  683.01   544.8  651.61   574.8  637.92   592.3  628.51
   594.8  627.19   604.8  625.47   617.3  626.67   634.7  628.28   744.6   630.7
   764.6  632.15   774.7  633.99   784.8  637.99     815  652.67  1016.6  742.66
  1046.8  755.68  1087.1  771.59  1137.5  798.43  1147.6  801.63  1177.8  805.46
#Mann= 3 , 0 , 0
       0     .06       0   592.3    .045       0   617.3     .06       0
Bank Sta=592.3,617.3
XS Rating Curve= 0 ,0
Exp/Cntr=0.3,0.1

Type RM Length L Ch R = 1 ,32960.3 ,297,298.9,301
XS GIS Cut Line= 4
     1532286.422      442684.073     1532684.478       442963.66
     1532959.326      443243.247     1533319.472       443499.14
#Sta/Elev= 30
    10.1   837.9    50.7  838.45   121.6  836.63   172.3   830.4   192.5  825.37
   222.9  813.02   283.8  792.72   314.2  778.01   334.4  771.04   344.6  765.06
   415.5  714.41   486.4  670.71   536.7  646.45   576.9  632.42   594.6  624.87
   607.1   622.3   619.6  623.34   647.3  625.67   767.9  624.79     788  628.04
   818.2   636.8   858.4  640.63   898.6  649.26   948.8  662.07    1009  682.34
  1169.7   728.6  1209.8  743.91  1270.1  775.42  1290.2  780.95  1320.3  785.36
#Mann= 3 , 0 , 0
    10.1     .06       0   594.6    .045       0   619.6     .06       0
#XS Ineff= 2 , 0
                          668.75          665.05
Permanent Ineff=
       F       F
Bank Sta=594.6,619.6
XS Rating Curve= 0 ,0
Exp/Cntr=0.3,0.1

Type RM Length L Ch R = 1 ,32661.4 ,393.8,410.1,426.4
XS GIS Cut Line= 3
     1532167.953      442788.326     1532546.406      443239.798
     1532897.722      443660.258
#Sta/Elev= 30
    10.2  846.62    40.6  847.25    71.1   845.4   101.6  840.05   152.4   832.5
   203.1  821.32   233.6   810.7   264.1  801.48   274.2  797.01   284.4  790.95
   335.2  753.72   396.1  716.24   436.8  694.96   467.2   672.9   477.4  666.73
   507.9  651.14   538.3  637.48   548.5  633.08   576.6  622.78   589.1  620.63
   601.6  621.56   619.6  622.29     650  621.37   690.6  623.39   761.6  623.68
   913.8  628.63   934.1  628.18   954.4  626.46   974.7  625.81    1137  627.36
#Mann= 3 , 0 , 0
    10.2     .06       0   576.6    .045       0   601.6     .06       0
#XS Ineff= 2 , 0
                          695.94          701.65
Permanent Ineff=
       F       F
Bank Sta=576.6,601.6
XS Rating Curve= 0 ,0
Exp/Cntr=0.3,0.1

Type RM Length L Ch R = 1 ,32251.3 ,241.5,192.6,143.6
XS GIS Cut Line= 4
     1531968.924      442750.415     1532157.855      443145.818
     1532187.619      443417.416      1532561.27      443887.719
#Sta/Elev= 30
      10  813.96    59.8  799.59   159.4  778.06   229.1  759.75   318.7  734.32
   348.6  723.53   418.3  702.77   438.2  694.99   468.6  680.66   488.8   671.9
   498.9  668.02   549.5  650.78     590  634.01   620.4  620.39   630.5  617.78
     643   618.6   660.8  621.49     671  621.93   791.5  622.26   951.7  625.86
  1051.8   630.2  1081.9  632.77  1121.9  637.58    1182  651.84    1212   655.8
    1232  660.92    1252  664.47  1262.1  667.13  1272.1  670.85  1312.1   687.5
#Mann= 3 , 0 , 0
      10     .06       0   620.4    .045       0     643     .06       0
Bank Sta=620.4,643
XS Rating Curve= 0 ,0
Exp/Cntr=0.3,0.1

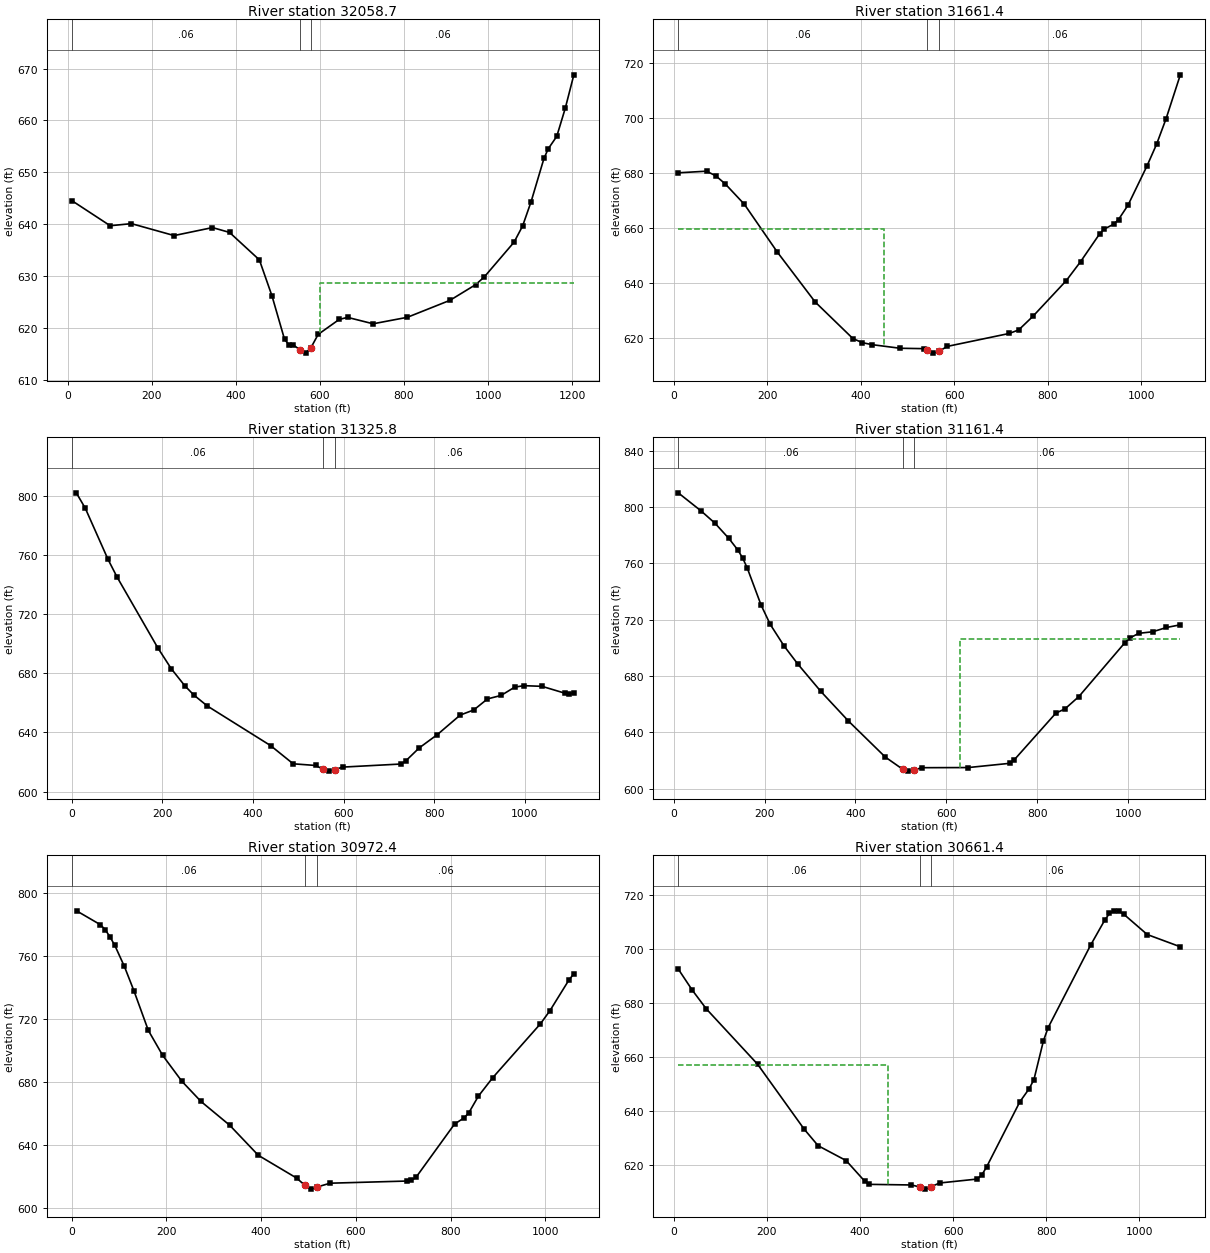
Type RM Length L Ch R = 1 ,32058.7 ,366,397.3,430.5
XS GIS Cut Line= 4
     1531592.336      443249.992     1531971.829      443502.988
     1532172.737      443443.459     1532488.981       443878.76
#Sta/Elev= 30
    10.1  644.55   101.4   639.7     152   640.1   253.4   637.8   344.6  639.34
   385.1  638.41   456.1  633.11     486  626.18     516  617.76   525.9  616.78
   535.9  616.76   553.4   615.7   565.9  615.12   578.4  616.12   595.8  618.73
   645.7  621.61   665.6  622.02   726.5  620.78   807.8  622.03   909.3  625.31
   970.2  628.33   990.5  629.79  1061.6  636.53  1081.9  639.65  1102.2  644.37
  1132.6  652.67  1142.8  654.54  1163.1  656.94  1183.4  662.39  1203.7  668.81
#Mann= 3 , 0 , 0
    10.1     .06       0   553.4    .045       0   578.4     .06       0
#XS Ineff= 2 , 0
                          599.98          628.56
Permanent Ineff=
       F       F
Bank Sta=553.4,578.4
XS Rating Curve= 0 ,0
Exp/Cntr=0.3,0.1

Type RM Length L Ch R = 1 ,31661.4 ,332.3,335.6,337
XS GIS Cut Line= 3
     1531528.219      443399.626     1531901.183      443810.451
     1532229.556      444224.171
#Sta/Elev= 30
    10.1  680.19    70.6  680.78    90.8  679.05     111  676.07   151.3  668.75
   221.9  651.31   302.7  633.16   383.4  619.83   403.5  618.35   423.7  617.63
   484.2   616.3   534.7  616.16   542.4  615.59   554.9  614.53   567.4  615.22
   585.3  616.99   717.4  621.69   737.7  622.98   768.2  627.95   839.3  640.92
   869.8   647.8   910.4  657.89   920.5  659.72   940.9  661.49     951  663.17
   971.3  668.39    1012  682.73  1032.3  690.56  1052.6  699.85  1083.1  715.87
#Mann= 3 , 0 , 0
    10.1     .06       0   542.4    .045       0   567.4     .06       0
#XS Ineff= 2 , 0
          450.76  659.78
Permanent Ineff=
       F       F
Bank Sta=542.4,567.4
XS Rating Curve= 0 ,0
Exp/Cntr=0.3,0.1

Type RM Length L Ch R = 1 ,31325.8 ,167.4,164.4,161.1
XS GIS Cut Line= 4
     1531310.236      443589.177     1531622.995      443977.755
     1531746.202      444157.829     1531987.879      444465.848
#Sta/Elev= 30
      10  802.08    29.9  791.62    79.8  757.22    99.8  745.22   189.5  697.46
   219.5  683.18   249.4  671.64   269.4  665.35   299.3   657.9     439  631.11
   488.8  618.81   538.5  617.67   555.7  615.02   568.2  613.85   580.7  614.95
     598  616.57     727  618.66   737.1  620.67   767.2  629.58   807.3   638.6
   857.5  651.74   887.7  655.25   917.8  662.69   947.9  665.05     978  670.67
   998.1  671.65  1038.2   671.2  1088.4  666.58  1098.5  666.01  1108.5  666.76
#Mann= 3 , 0 , 0
       0     .06       0   555.7    .045       0   580.7     .06       0
Bank Sta=555.7,580.7
XS Rating Curve= 0 ,0
Exp/Cntr=0.3,0.1

Type RM Length L Ch R = 1 ,31161.4 ,195.2,189,183.2
XS GIS Cut Line= 3
     1531172.812      443707.646     1531510.721      444098.029
      1531907.32      444546.407
#Sta/Elev= 30
    10.1  810.09    60.7  797.15    91.1  788.46   121.5  777.72   141.7   769.3
   151.9  763.78     162  756.68   192.4  730.41   212.6  716.65     243  701.35
   273.3  688.49     324  669.05   384.7  648.05   465.7   622.5   503.8  613.88
   516.3   612.5   528.8   613.4   546.8  614.94   648.2  615.03   739.5  618.04
   749.7   620.6     841  653.66   861.3  656.74   891.7  665.45   993.2  703.79
  1003.3  706.95  1023.6  710.35    1054  711.43  1084.5  714.48  1114.9  716.39
#Mann= 3 , 0 , 0
    10.1     .06       0   503.8    .045       0   528.8     .06       0
#XS Ineff= 2 , 0
                          630.46          706.23
Permanent Ineff=
       F       F
Bank Sta=503.8,528.8
XS Rating Curve= 0 ,0
Exp/Cntr=0.3,0.1

Type RM Length L Ch R = 1 ,30972.4 ,304.8,311,316.8
XS GIS Cut Line= 4
     1530992.739      443949.323     1531329.191         444191.
     1531665.643      444432.677     1531840.978      444584.317
#Sta/Elev= 30
    10.1  788.85    60.6     780    70.7  776.86    80.8  772.22    90.9  766.86
   111.1   753.5   131.3  737.97   161.7  712.79     192  696.92   232.4  680.52
   272.8  667.66   333.4  652.55     394  633.39   474.9  618.91   492.7  614.22
   505.2  611.89   517.7  613.21   545.6  615.66   707.3  617.03   717.4  617.43
   727.5  619.61   808.3  653.24   828.5   657.2   838.6  660.48   858.7  671.01
     889  682.76   989.8  717.03  1009.9   725.4  1050.2     745  1060.3  748.82
#Mann= 3 , 0 , 0
       0     .06       0   492.7    .045       0   517.7     .06       0
Bank Sta=492.7,517.7
XS Rating Curve= 0 ,0
Exp/Cntr=0.3,0.1

Type RM Length L Ch R = 1 ,30661.4 ,187.2,184.3,181.8
XS GIS Cut Line= 3
     1530893.225      444082.008     1531248.231      444489.603
     1531613.517      444897.076
#Sta/Elev= 30
      10  692.59      40  684.79    70.1  677.85   180.2  657.32   280.3  633.22
   310.3  627.08   370.4  621.57   410.4   613.9   420.4  612.75   510.5  612.52
     528  611.81   540.5  610.98     553  611.88   570.9  613.25     652  614.72
   662.1  616.35   672.3  619.32   743.2  643.32   763.5  648.25   773.6  651.62
   793.9  665.93     804  670.84   895.2  701.43   925.6  710.73   935.7  713.19
   945.9  714.17     956  714.01   966.1  712.96  1016.8  705.38  1087.8  700.84
#Mann= 3 , 0 , 0
      10     .06       0     528    .045       0     553     .06       0
#XS Ineff= 2 , 0
           459.9  657.14
Permanent Ineff=
       F       F
Bank Sta=528,553
XS Rating Curve= 0 ,0
Exp/Cntr=0.3,0.1

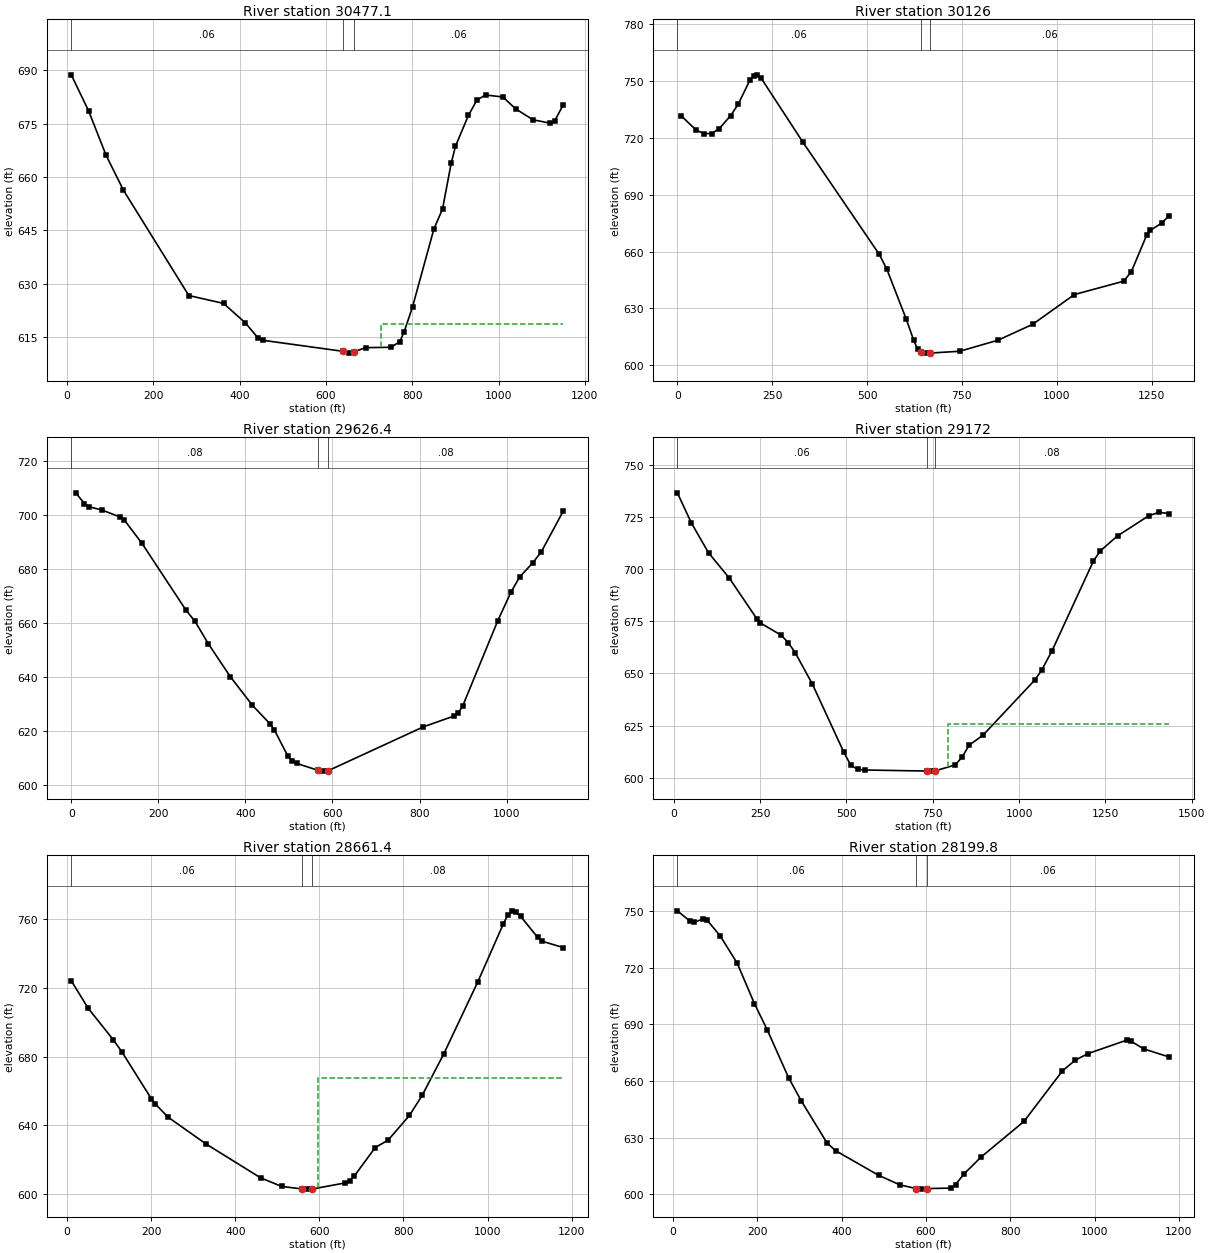
Type RM Length L Ch R = 1 ,30477.1 ,366.7,351.1,331.1
XS GIS Cut Line= 4
     1530833.889      444071.869      1531047.48      444550.781
     1531272.753      444757.697      1531547.69      444920.505
#Sta/Elev= 30
    10.1  688.75    50.4  678.57    90.8  666.09   131.1  656.24   282.4  626.62
     363   624.4   413.5  618.92   443.7  614.53   453.8  614.03   640.2  610.91
   652.7  610.41   665.2  610.82   692.1  611.95   751.3  612.06   771.1  613.66
   780.9  616.27   800.7  623.44   850.2  645.36   870.2  650.99   890.2  663.84
   900.2  668.65   930.1  677.32   950.1  681.69   970.1  683.08    1010  682.51
    1040  679.13  1079.9  676.09  1119.8  675.14  1129.8  675.74  1149.8   680.3
#Mann= 3 , 0 , 0
    10.1     .06       0   640.2    .045       0   665.2     .06       0
#XS Ineff= 2 , 0
                          728.36          618.71
Permanent Ineff=
       F       F
Bank Sta=640.2,665.2
XS Rating Curve= 0 ,0
Exp/Cntr=0.3,0.1

Type RM Length L Ch R = 1 ,30126   ,495.7,499.6,505.7
XS GIS Cut Line= 4
     1530296.141      444664.876     1530784.233      444849.688
     1531172.812      444916.031      1531534.42      445034.183
#Sta/Elev= 30
      10  731.68    50.2  723.99    70.3  722.29    90.3  722.29   110.4  724.92
   140.5  731.75   160.6  737.91   190.7  750.36   200.7  752.95   210.8  753.31
   220.8  751.54   331.2  717.62     532  658.52   552.2  650.57   602.8  624.48
     623  613.01   633.1  608.47   640.8  607.05   653.3  606.33   665.8  606.36
   744.3  607.32   845.4  613.19   936.1  621.52  1046.3  637.27  1176.4  644.33
  1196.4  649.38  1236.5  668.48  1246.5  671.15  1276.5  675.07  1296.5  679.01
#Mann= 3 , 0 , 0
       0     .06       0   640.8    .045       0   665.8     .06       0
Bank Sta=640.8,665.8
XS Rating Curve= 0 ,0
Exp/Cntr=0.3,0.1

Type RM Length L Ch R = 1 ,29626.4 ,449.8,454.4,454.9
XS GIS Cut Line= 3
     1530394.805      445186.099     1530950.949      445303.101
     1531499.787      445423.079
#Sta/Elev= 30
    10.1   708.2    30.4  704.22    40.6  703.06      71  701.79   111.6  699.29
   121.8  698.14   162.4  689.49   263.9  664.65   284.2  660.63   314.6  652.36
   365.3  640.11   416.1   629.5   456.7  622.61   466.8   620.3   497.3  610.76
   507.4  608.89   517.6  607.98   565.9  605.48   578.4  605.12   590.9  605.33
   809.1  621.54   879.3  625.53   889.3  626.71   899.4  629.35   979.6  660.77
  1009.7  671.29  1029.8  677.01  1059.9  682.22    1080  686.41  1130.1  701.44
#Mann= 3 , 0 , 0
       0     .08       0   565.9    .045       0   590.9     .08       0
Bank Sta=565.9,590.9
XS Rating Curve= 0 ,0
Exp/Cntr=0.3,0.1

Type RM Length L Ch R = 1 ,29172   ,502.7,510.6,506.2
XS GIS Cut Line= 4
     1530324.573      445247.744     1530646.809      445451.511
     1531134.387      445736.567     1531490.309      446072.289
#Sta/Elev= 30
      10  736.48    50.2  722.15   100.3  707.78   160.5  695.66   240.8  676.04
   250.8  674.14     311   668.3   331.1  664.79   351.2  660.03   401.4  644.85
   492.2  612.34   512.4  606.07   532.5   604.1   552.7   603.8   731.8   603.3
   744.3  603.26   756.8  603.39   814.9  606.21   835.1  610.02   855.3  615.68
   895.6  620.49  1045.9  646.94  1065.9  651.71  1095.8  660.99  1215.6  703.91
  1235.6  708.73  1285.5   715.9  1375.4  725.47  1405.4  727.15  1435.3  726.55
#Mann= 3 , 0 , 0
      10     .06       0   731.8    .045       0   756.8     .08       0
#XS Ineff= 2 , 0
                          794.28          625.64
Permanent Ineff=
       F       F
Bank Sta=731.8,756.8
XS Rating Curve= 0 ,0
Exp/Cntr=0.3,0.1

Type RM Length L Ch R = 1 ,28661.4 ,344.2,461.6,441.9
XS GIS Cut Line= 3
     1530273.039      445401.927     1530627.183      445849.209
     1530991.326      446338.008
#Sta/Elev= 30
      10  724.23      50  708.28   110.1  689.82   130.1  682.95   200.2  655.67
   210.2  652.42   240.2  644.84   330.3  629.27   460.4  609.51   510.5  604.52
     558  603.09   570.5  602.95     583  603.01   661.9  606.59   672.1  607.89
   682.3  610.31     733  627.17   763.5  631.45   814.3  645.82   844.8  657.63
   895.6   681.5   976.9  723.61  1037.8  757.46    1048  762.39  1058.1  764.92
  1068.3  763.96  1078.4  761.79  1119.1   749.5  1129.2  747.26    1180  743.55
#Mann= 3 , 0 , 0
      10     .06       0     558    .045       0     583     .08       0
#XS Ineff= 2 , 0
                          596.95          667.91
Permanent Ineff=
       F       F
Bank Sta=558,583
XS Rating Curve= 0 ,0
Exp/Cntr=0.3,0.1

Type RM Length L Ch R = 1 ,28199.8 ,492.4,475.9,454
XS GIS Cut Line= 3
     1530093.773      445562.631     1530508.747      446049.424
     1530844.189      446469.597
#Sta/Elev= 30
    10.2  750.22    40.6  744.67    50.8   744.2    71.1  745.94    81.2  745.16
   111.7  736.97   152.3  722.38   192.9  701.06   223.4  687.11   274.1  661.69
   304.6  649.25   365.5  627.03   385.8  622.99   487.4  609.97   538.1  604.88
   576.4  602.95  588.44  602.62   601.4  602.92     660  603.17   670.1  605.04
   690.4  610.72     731  619.69   832.4  638.51   923.7  665.34   954.1  671.01
   984.6  674.52  1075.9   681.6    1086  681.13  1116.4  677.01  1177.3  672.66
#Mann= 3 , 0 , 0
    10.2     .06       0   576.4    .045       0   601.4     .06       0
Bank Sta=576.4,601.4
XS Rating Curve= 0 ,0
Exp/Cntr=0.3,0.1

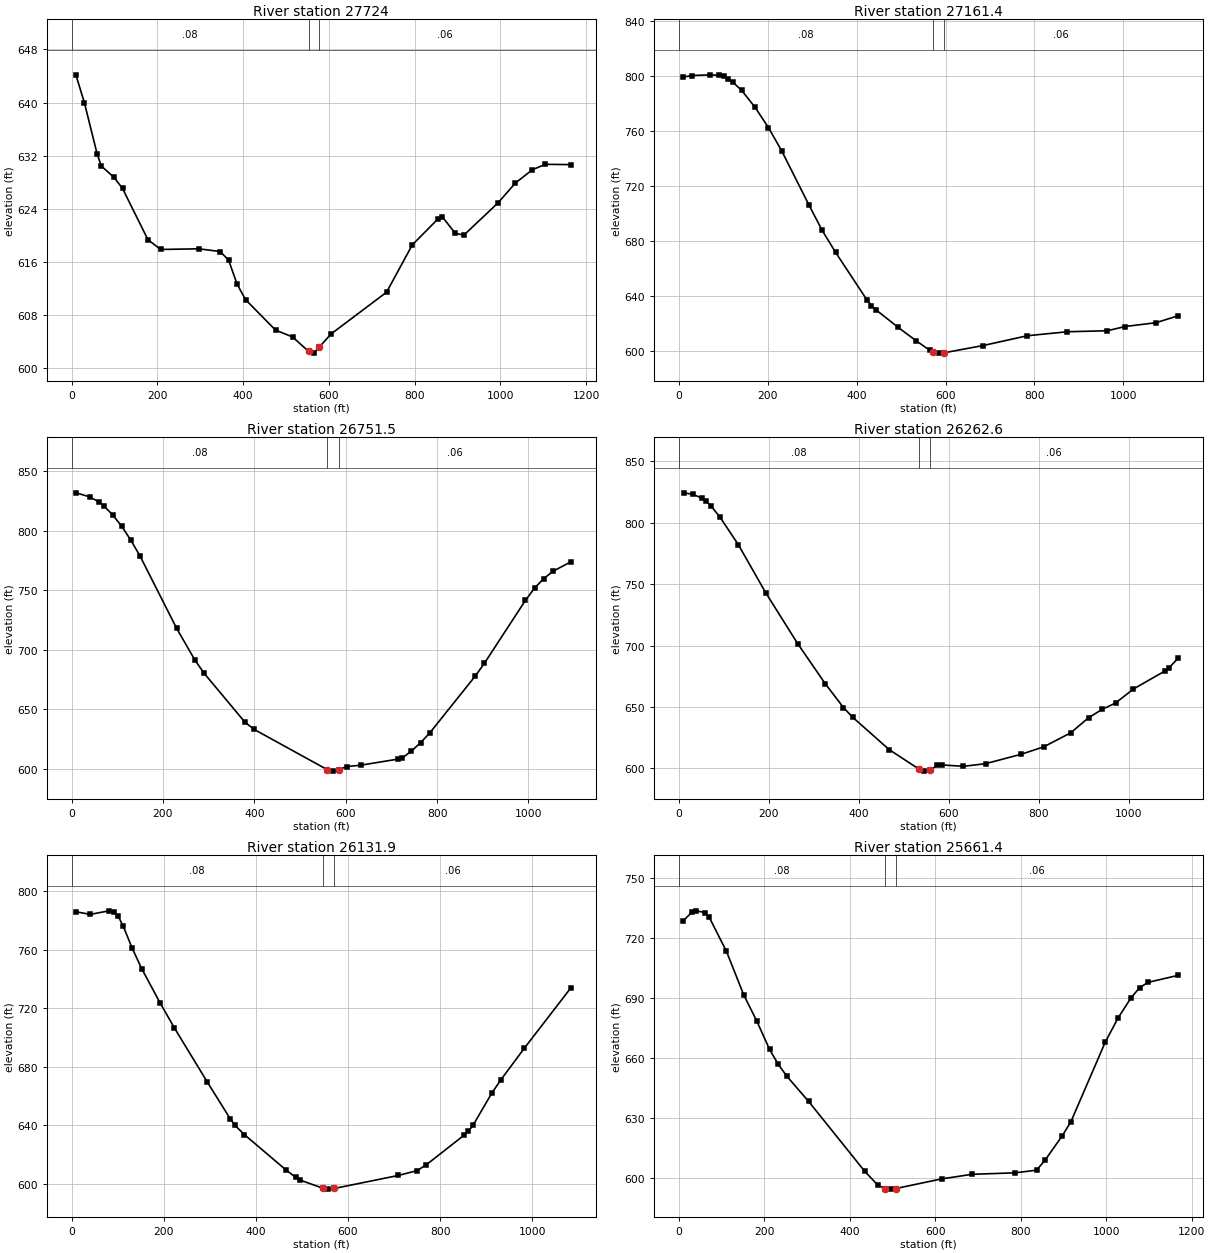
Type RM Length L Ch R = 1 ,27724   ,528.9,562.6,566.3
XS GIS Cut Line= 4
     1529855.435      445968.037     1530130.284      446209.714
     1530504.646      446313.966     1530746.323       446645.68
#Sta/Elev= 30
     9.9  644.18    29.7  639.99    59.3  632.32    69.2  630.46    98.9  628.75
   118.7  627.08     178  619.37   207.7   617.9   296.7     618   346.2  617.59
     366  616.33   385.9  612.69   405.8  610.34   475.6  605.77   515.5  604.73
   552.8  602.56   565.3   602.3   577.8  603.21   605.1  605.18   734.7  611.47
   794.6  618.58   854.7   622.5   864.7  622.81   894.7  620.36   914.8  620.04
   994.8  624.92  1034.9  627.88  1074.9   629.9    1105  630.71    1165  630.67
#Mann= 3 , 0 , 0
       0     .08       0   552.8    .045       0   577.8     .06       0
Bank Sta=552.8,577.8
XS Rating Curve= 0 ,0
Exp/Cntr=0.3,0.1

Type RM Length L Ch R = 1 ,27161.4 ,406.6,409.9,411.6
XS GIS Cut Line= 3
     1529635.595      446353.379     1530120.422      446679.618
     1530558.913      446993.836
#Sta/Elev= 30
    10.1  799.56    30.2  800.65    70.5  801.14    90.7  800.83   100.8  799.95
   110.8  798.17   120.9  795.88   141.1  789.88   171.3   777.5   201.5  762.75
   231.7  745.53   292.2  706.65   322.4  687.85   352.6  671.87   423.2  637.21
   433.2  633.16   443.3  630.08   493.7   617.2     534  607.49   564.2  600.66
   571.9  599.39   584.4  598.52   596.9  598.78   684.3  604.04   784.2  611.19
   874.1  614.08     964  614.82  1003.9  617.88  1073.9  620.69  1123.8  625.76
#Mann= 3 , 0 , 0
       0     .08       0   571.9    .045       0   596.9     .06       0
Bank Sta=571.9,596.9
XS Rating Curve= 0 ,0
Exp/Cntr=0.3,0.1

Type RM Length L Ch R = 1 ,26751.5 ,473.7,488.9,498.3
XS GIS Cut Line= 4
     1529525.702      446488.377     1529746.444      446821.014
     1529997.598      447010.565     1530163.455      447351.756
#Sta/Elev= 30
      10  831.88    39.9  828.42    59.9  824.21    69.9  821.14    89.8  813.38
   109.8  803.64   129.7  792.03   149.7  778.79   229.6  718.19   269.5  691.56
   289.4  680.55   379.3  639.19   399.2  633.16   559.3  599.34   571.8  598.04
   584.3   599.2   602.2  601.88   632.7  603.01   713.9  608.11   723.9  609.16
   743.8  614.87   763.8  621.92   783.8  630.04   883.6  677.94   903.6  688.68
   993.4  741.52  1013.4  751.87  1033.3  759.72  1053.3  765.89  1093.2  773.96
#Mann= 3 , 0 , 0
       0     .08       0   559.3    .045       0   584.3     .06       0
Bank Sta=559.3,584.3
XS Rating Curve= 0 ,0
Exp/Cntr=0.3,0.1

Type RM Length L Ch R = 1 ,26262.6 ,123.1,130.7,139
XS GIS Cut Line= 4
     1529378.628      446557.532     1529527.449      447011.436
     1529624.182      447156.536      1529966.47      447461.618
#Sta/Elev= 30
    10.2  824.29    30.5  823.13    50.8  820.06      61  817.45    71.1  813.76
    91.5  804.39   132.1  782.09   193.1  742.91   264.2  701.47   325.2  669.03
   365.9   649.5   386.2  641.64   467.5  615.29     533  599.58   545.5  597.73
     558  598.48   574.6  602.32   584.2  602.79   632.7  601.64     682  603.79
   761.7  611.52   811.5  617.54   871.4  628.93   911.2  641.27   941.1  647.97
     971  653.18  1010.9   664.6  1080.7  679.21  1090.6  682.03  1110.6  689.82
#Mann= 3 , 0 , 0
       0     .08       0     533    .045       0     558     .06       0
Bank Sta=533,558
XS Rating Curve= 0 ,0
Exp/Cntr=0.3,0.1

Type RM Length L Ch R = 1 ,26131.9 ,488.1,470.5,453.5
XS GIS Cut Line= 3
     1529286.784      446598.292     1529455.309      447129.508
     1529599.542      447636.082
#Sta/Elev= 30
    10.1  785.77    40.5  784.01    81.1  786.44    91.2  785.73   101.3  782.58
   111.5   776.3   131.7  760.77     152  747.02   192.5  723.32   222.9  706.63
   293.9  669.93   344.5  644.43   354.6  640.08   374.9  633.77   466.1  609.42
   486.4   604.6   496.5  602.67   544.8  597.24   557.3  596.56   569.8  596.99
   709.2  605.89   749.8  609.19     770   613.2     851  633.15   861.2  636.03
   871.3  640.11   911.8  661.95   932.1  671.33   982.7  692.72    1084  734.03
#Mann= 3 , 0 , 0
       0     .08       0   544.8    .045       0   569.8     .06       0
Bank Sta=544.8,569.8
XS Rating Curve= 0 ,0
Exp/Cntr=0.3,0.1

Type RM Length L Ch R = 1 ,25661.4 ,522.8,508.8,493.2
XS GIS Cut Line= 3
     1528642.312      446996.348     1529035.426      447280.868
     1529570.031      447706.668
#Sta/Elev= 30
    10.1  728.53    30.3  732.79    40.4  733.49    60.7  732.65    70.8  730.35
   111.2   713.3   151.6  691.58     182  678.58   212.3   664.3   232.5  656.89
   252.7  650.93   303.3  638.45   434.7  603.56   465.1  596.71   482.8  594.82
   495.3  594.62   507.8  594.93   615.9  599.77   686.3  602.02   786.8  602.75
   837.1  604.09   857.2  609.17   897.4  621.32   917.5  628.33   997.9  668.04
    1028  680.11  1058.2  690.11  1078.3  695.18  1098.4  697.83  1168.7   701.3
#Mann= 3 , 0 , 0
       0     .08       0   482.8    .045       0   507.8     .06       0
Bank Sta=482.8,507.8
XS Rating Curve= 0 ,0
Exp/Cntr=0.3,0.1