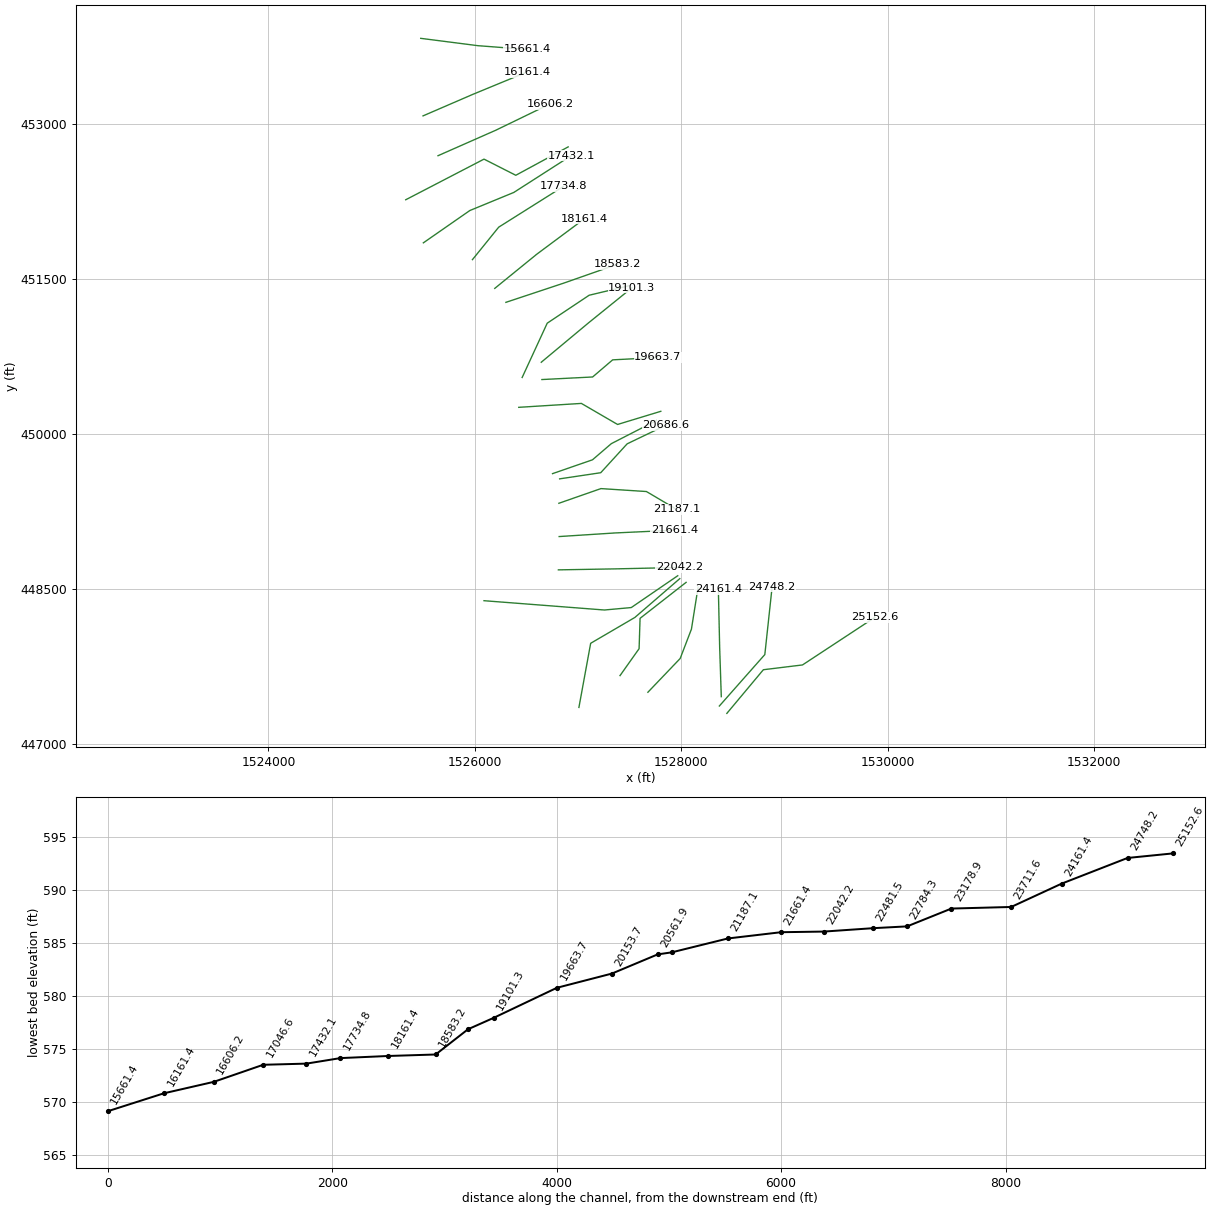
HEC-RAS study GRAGSTNCR.prj: GRAGSTNCR

--- GRAGSTNCR.g01 (geometry) --- (continued)

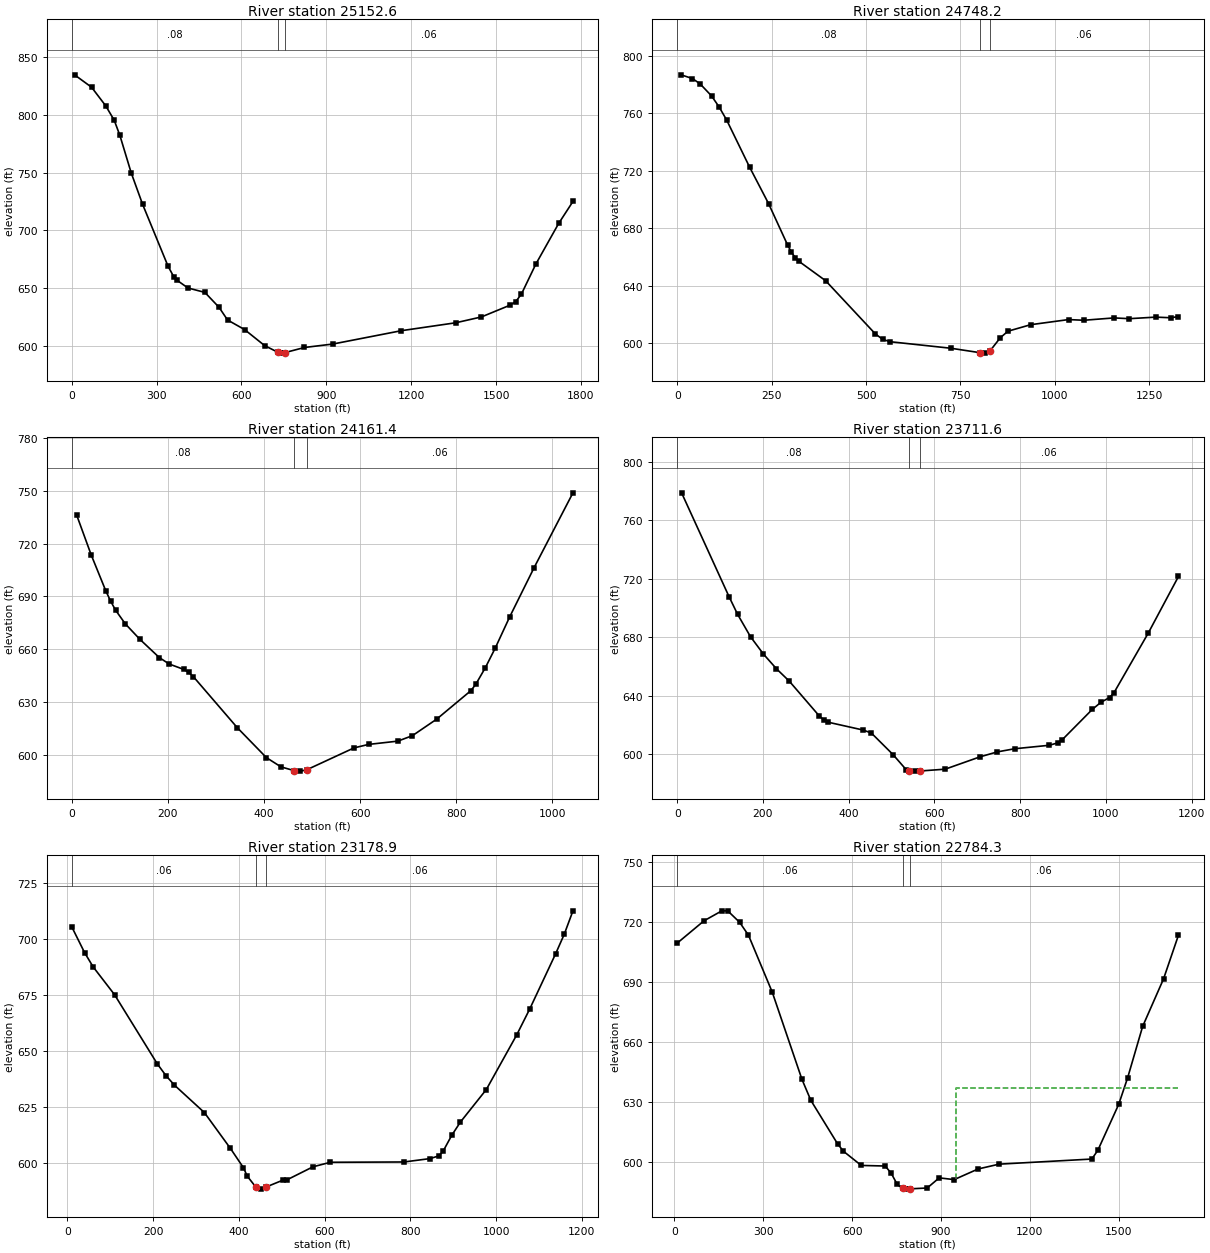
Type RM Length L Ch R = 1 ,25152.6 ,367,404.4,441.7
XS GIS Cut Line= 4
     1528440.445      447298.889     1528793.952      447721.379
     1529173.217      447767.787      1529874.39      448228.427
#Sta/Elev= 30
      10  834.69    70.1  823.94   120.2  807.82   150.2  795.32   170.3  782.12
   210.3  749.69   250.4  722.52   340.5   668.8   360.6  659.69   370.6   656.9
   410.7  649.94   470.7   646.1   520.8  633.16   550.9  622.18   611.2  613.86
   681.6  600.05   729.4  594.12   741.9  593.46   754.4  593.95   822.4  598.34
   922.9  601.33  1165.5  612.92  1357.5  619.77  1448.5  624.84  1549.5  635.02
  1569.8  638.13    1590  644.77  1640.5  670.55  1721.4  705.87  1771.9  724.93
#Mann= 3 , 0 , 0
       0     .08       0   729.4    .045       0   754.4     .06       0
Bank Sta=729.4,754.4
XS Rating Curve= 0 ,0
Exp/Cntr=0.3,0.1

Type RM Length L Ch R = 1 ,24748.2 ,583.7,586.8,577.1
XS GIS Cut Line= 3
     1528367.686      447370.085     1528808.168      447868.281
      1528879.25       448526.97
#Sta/Elev= 30
    10.1  786.72    40.3  784.12    60.5  780.43    90.7  772.08   110.8  764.39
     131  755.18   191.4  722.58   241.8  697.12   292.2  668.29   302.3  663.29
   312.3  659.54   322.4  656.89     393  643.42   523.9  606.61   544.1  602.56
   564.2  600.96   725.2  596.41   803.1  593.29   815.6  593.03   828.1  594.49
   855.7  603.77   875.8  608.28     936  612.82  1036.4  616.38  1076.6   615.9
  1156.9  617.54    1197     617  1267.3  618.09  1307.4  617.64  1327.5  618.51
#Mann= 3 , 0 , 0
       0     .08       0   803.1    .045       0   828.1     .06       0
Bank Sta=803.1,828.1
XS Rating Curve= 0 ,0
Exp/Cntr=0.3,0.1

Type RM Length L Ch R = 1 ,24161.4 ,451.1,449.8,440.9
XS GIS Cut Line= 3
     1528386.418      447460.747     1528370.761      447936.525
     1528357.986      448503.276
#Sta/Elev= 30
    10.1  736.38    40.5  713.59    70.9  693.13      81  687.24    91.2  682.17
   111.4   674.4   141.8  665.58   182.3  655.18   202.6  651.56     233  648.47
   243.1  646.82   253.2   644.3   344.4  615.34   405.1  598.28   435.5  593.02
   463.5  590.84     476  590.61   488.5  591.31   587.4  603.83   617.8  605.81
   678.5  607.67   708.9  610.78   759.5   620.2   830.3  636.33   840.5  639.89
   860.7  649.48     881  660.47   911.3  678.36   961.9  706.25  1042.9  748.89
#Mann= 3 , 0 , 0
       0     .08       0   463.5    .045       0   488.5     .06       0
Bank Sta=463.5,488.5
XS Rating Curve= 0 ,0
Exp/Cntr=0.3,0.1

Type RM Length L Ch R = 1 ,23711.6 ,518,532.8,540.8
XS GIS Cut Line= 4
     1527675.604      447503.396     1527988.362      447830.371
     1528097.354      448114.697     1528161.958      448521.846
#Sta/Elev= 30
    10.1  778.82   120.7  707.84   140.8  695.66   170.9  680.35   201.1  668.47
   231.3  658.47   261.4  649.94   331.8  625.97   341.9  623.43   351.9  621.88
   432.4   616.6   452.5  614.55   503.2  599.76   533.7  589.51   541.5  588.67
     554  588.41   566.5   588.5     625  589.75   706.2  598.18   746.8  601.59
   787.1  603.72   867.6  606.09   887.7  607.75   897.7  609.78   968.1  630.63
   988.2  635.48  1008.3  638.73  1018.4  641.87  1098.8  682.92  1169.2  721.61
#Mann= 3 , 0 , 0
       0     .08       0   541.5    .045       0   566.5     .06       0
Bank Sta=541.5,566.5
XS Rating Curve= 0 ,0
Exp/Cntr=0.3,0.1

Type RM Length L Ch R = 1 ,23178.9 ,422.5,394.6,366.8
XS GIS Cut Line= 4
     1527405.494      447664.514     1527590.306      447925.146
     1527599.784       448218.95     1528045.755       448567.15
#Sta/Elev= 30
      10   705.5    39.9  693.97    59.9  687.58   109.8  675.17   209.7  644.21
   229.6  639.03   249.6  634.73   319.5  622.46   380.3  606.43   410.7   597.8
   419.3   594.1   438.8  589.35  451.23  588.26   463.8  589.24     502  592.22
  513.06   592.5   572.9  598.24   613.5  600.26   785.2  600.39   845.8   601.9
   866.1  603.09   876.2  605.14   896.4  612.26   916.6  618.19   977.2  632.77
  1047.9   657.1  1078.2  668.64  1138.9  693.43  1159.1  702.19  1179.3  712.61
#Mann= 3 , 0 , 0
      10     .06       0   438.8    .045       0   463.8     .06       0
Bank Sta=438.8,463.8
XS Rating Curve= 0 ,0
Exp/Cntr=0.3,0.1

Type RM Length L Ch R = 1 ,22784.3 ,315.3,302.7,289.9
XS GIS Cut Line= 4
     1527007.438      447356.495     1527121.168      447977.273
     1527549.063      448227.231     1527984.315      448603.057
#Sta/Elev= 30
      10  709.34   100.2  720.45   160.3  725.42   180.3  725.44   220.4  719.73
   250.4  713.26   330.6  684.86   430.8  641.38   460.8  630.89     551   609.2
     571  605.46   631.1   598.4     712  598.11   732.2  594.46   752.5  588.93
   770.3   586.9  782.64  586.58   795.3  586.72   853.6  587.14   894.1   592.2
   944.6  591.33  1025.5  596.64  1096.3  599.04  1409.1  601.59  1429.3  605.89
  1499.9  628.86  1530.2  642.19  1580.7  667.75  1651.3   691.5  1701.7  713.32
#Mann= 3 , 0 , 0
      10     .06       0   770.3    .045       0   795.3     .06       0
#XS Ineff= 2 , 0
                          952.33          636.95
Permanent Ineff=
       F       F
Bank Sta=770.3,795.3
XS Rating Curve= 0 ,0
Exp/Cntr=0.3,0.1

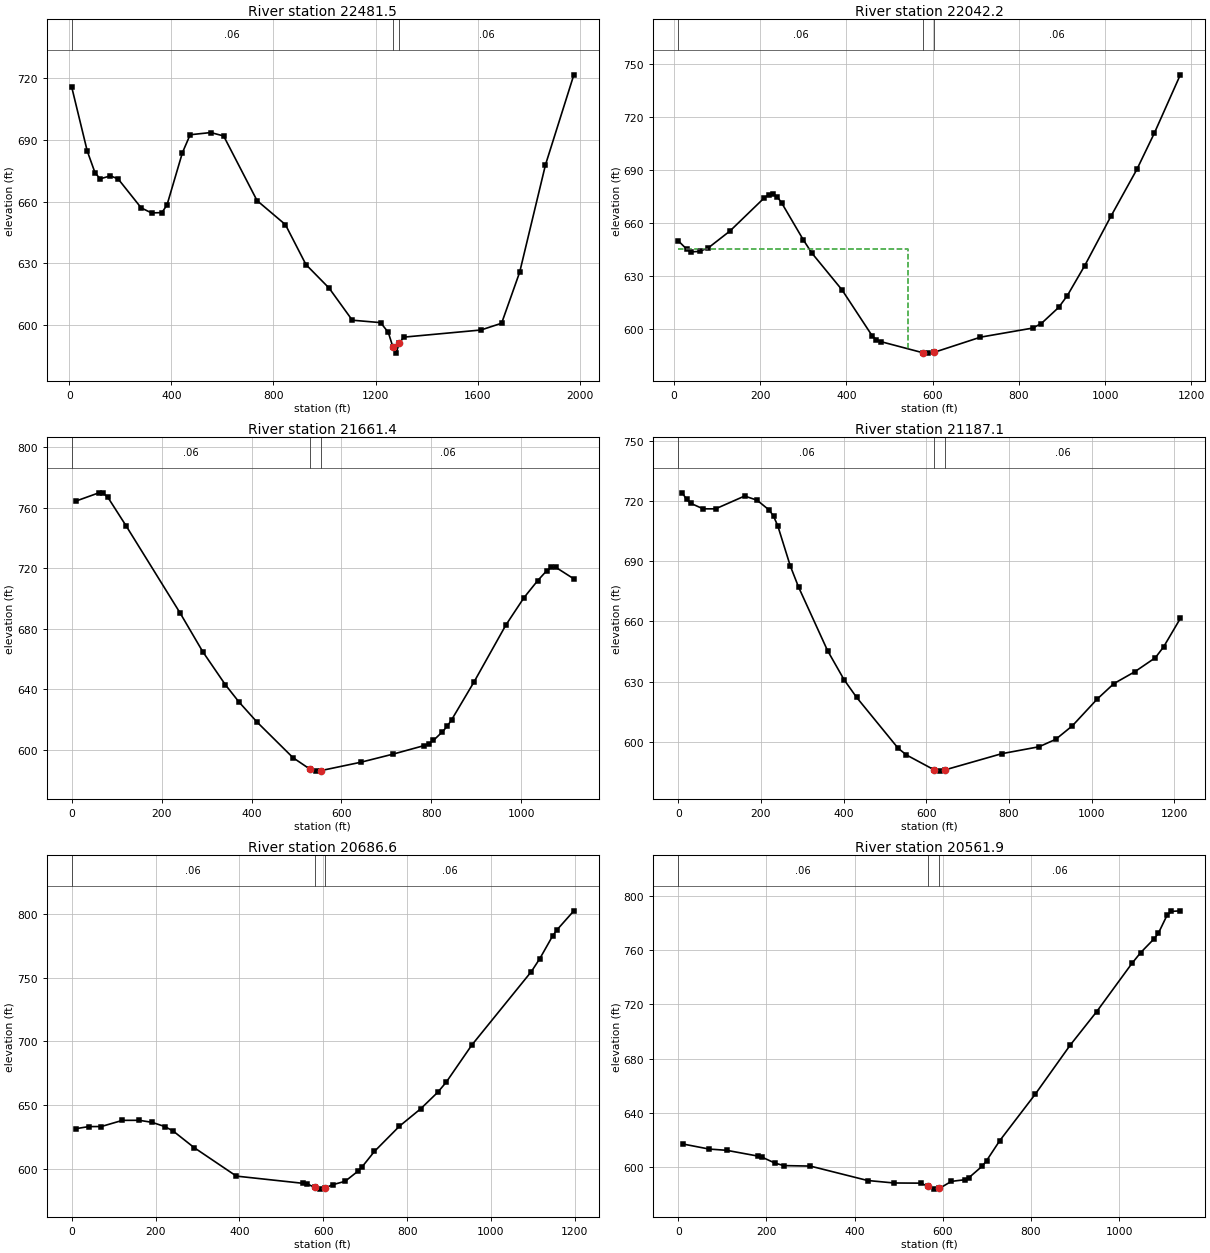
Type RM Length L Ch R = 1 ,22481.5 ,444.1,439.3,430.8
XS GIS Cut Line= 4
     1526088.118      448389.545     1527253.854      448299.509
     1527514.486      448323.203     1527964.668      448631.222
#Sta/Elev= 30
    10.1  715.49    70.6  684.59   100.8  674.11     121  671.04   161.3  672.48
   191.5  671.03   282.2  656.92   322.5  654.49   362.9  654.64     383  658.33
   443.5  683.78   473.7  692.45   554.4  693.52   604.8  691.87   735.8  660.47
   846.7  648.82   927.3   629.4    1018  617.97  1108.7   602.4  1219.5  601.22
  1249.7  596.49  1267.4  589.52 1279.99  586.41  1292.4   591.1  1310.1  594.17
  1612.7  597.64  1693.5  600.93  1764.3  625.73  1865.3  677.85  1976.4  721.55
#Mann= 3 , 0 , 0
    10.1     .06       0  1267.4    .045       0  1292.4     .06       0
Bank Sta=1267.4,1292.4
XS Rating Curve= 0 ,0
Exp/Cntr=0.3,0.1

Type RM Length L Ch R = 1 ,22042.2 ,377.1,380.8,387.4
XS GIS Cut Line= 3
      1526808.41      448688.088     1527358.106      448697.565
     1527982.589      448711.406
#Sta/Elev= 30
      10   649.7      30  644.85      40   643.4      60  643.71      80  645.73
   129.9  655.22   209.9  674.08   219.9  675.83   229.9  676.26   239.9  674.54
   249.9  671.11   299.9   650.3   319.9  642.74   389.8  621.91   459.8  595.88
   469.8  593.66   479.8   592.6   577.6  586.29   590.1  586.09   602.6  586.48
     711  595.13   831.9  600.27     852  602.84   892.3  611.98   912.5   618.7
   952.8  635.66  1013.2  663.46  1073.7  690.13    1114  710.56  1174.4  743.66
#Mann= 3 , 0 , 0
      10     .06       0   577.6    .045       0   602.6     .06       0
#XS Ineff= 2 , 0
          542.13  645.27
Permanent Ineff=
       F       F
Bank Sta=577.6,602.6
XS Rating Curve= 0 ,0
Exp/Cntr=0.3,0.1

Type RM Length L Ch R = 1 ,21661.4 ,477.1,474.3,471.7
XS GIS Cut Line= 3
       1526816.1      449010.514     1527357.546      449045.377
     1527931.497      449071.927
#Sta/Elev= 30
      10   764.4    60.3  769.76    70.3  769.46    80.4  766.74   120.6  748.09
   241.1  690.39   291.4   664.9   341.6  643.13   371.8  631.76   411.9  618.51
   492.3  594.89   530.1   587.3   542.6  586.03   555.1  586.42   643.4  591.92
   713.9  597.18   784.5  602.93   794.6  604.15   804.6  606.28   824.8  612.03
   834.9   615.5     845  619.86   895.4  645.11   965.9   682.5  1006.3  700.61
  1036.5  711.75  1056.7  718.33  1066.7  720.51  1076.8  720.61  1117.1  712.96
#Mann= 3 , 0 , 0
       0     .06       0   530.1    .045       0   555.1     .06       0
Bank Sta=530.1,555.1
XS Rating Curve= 0 ,0
Exp/Cntr=0.3,0.1

Type RM Length L Ch R = 1 ,21187.1 ,470.2,500.5,526.3
XS GIS Cut Line= 4
     1526813.149       449332.56     1527220.682      449474.722
     1527661.387       449446.29     1527955.589      449272.567
#Sta/Elev= 30
      10  724.01    20.1  720.69    30.1   718.8    60.2  716.04    90.3  716.03
   160.6  722.41   190.7  720.35   220.8  715.31   230.9  712.26   240.9  707.55
     271   687.7   291.1  677.11   361.4  645.41   401.5  630.89   431.6  622.17
     532  596.86   552.1   593.5   619.9  586.01   632.4  585.44   644.9  586.02
   782.9  594.13   873.2  597.58   913.4  601.27   953.6  607.99  1013.9  621.34
  1054.1  629.01  1104.4  634.88  1154.6  641.92  1174.7  647.38  1214.9  661.45
#Mann= 3 , 0 , 0
       0     .06       0   619.9    .045       0   644.9     .06       0
Bank Sta=619.9,644.9
XS Rating Curve= 0 ,0
Exp/Cntr=0.3,0.1

Type RM Length L Ch R = 1 ,20686.6 ,128.2,124.7,121.2
XS GIS Cut Line= 4
     1526820.416      449568.963     1527218.646      449628.399
     1527474.539      449907.986     1527849.615      450087.838
#Sta/Elev= 30
    10.1  631.54    40.3  633.15    70.5  633.21   120.8  638.05   161.1  638.08
   191.3  636.51   221.5  633.23   241.6  629.75   291.9  616.67   392.6  594.34
   552.3  588.66   562.2  588.17   579.6  585.42   592.1  584.13   604.6  585.07
   622.1  587.58     652  590.26   681.9  598.01   691.9  601.34   721.8  613.64
   781.7   633.5   832.4  647.15     873  660.08   893.3  668.03   954.1  697.04
  1096.2  754.67  1116.5   764.9  1146.9  782.59    1157  787.27  1197.6  802.32
#Mann= 3 , 0 , 0
       0     .06       0   579.6    .045       0   604.6     .06       0
Bank Sta=579.6,604.6
XS Rating Curve= 0 ,0
Exp/Cntr=0.3,0.1

Type RM Length L Ch R = 1 ,20561.9 ,442,408.2,375.6
XS GIS Cut Line= 4
     1526751.943      449619.519     1527138.876      449753.457
     1527321.182      449909.719     1527756.482       450132.95
#Sta/Elev= 30
      10   617.2    69.9  613.45   109.9  612.51   179.8  608.33   189.7  607.53
   219.7  603.05   239.7  601.27   299.6   600.9   429.5  590.29   489.5  588.46
   549.5  588.35     567     586   579.5  583.94     592  584.43   619.6  589.64
   649.6  590.85   659.6  592.45   689.5  600.86   699.5  604.98   729.4  619.69
   809.3  653.63   889.2  690.03   949.1  714.61    1029   750.1  1048.9  758.09
  1078.9  768.09  1088.9  772.25  1108.8  785.64  1118.8  788.42  1138.8  788.84
#Mann= 3 , 0 , 0
       0     .06       0     567    .045       0     592     .06       0
Bank Sta=567,592
XS Rating Curve= 0 ,0
Exp/Cntr=0.3,0.1

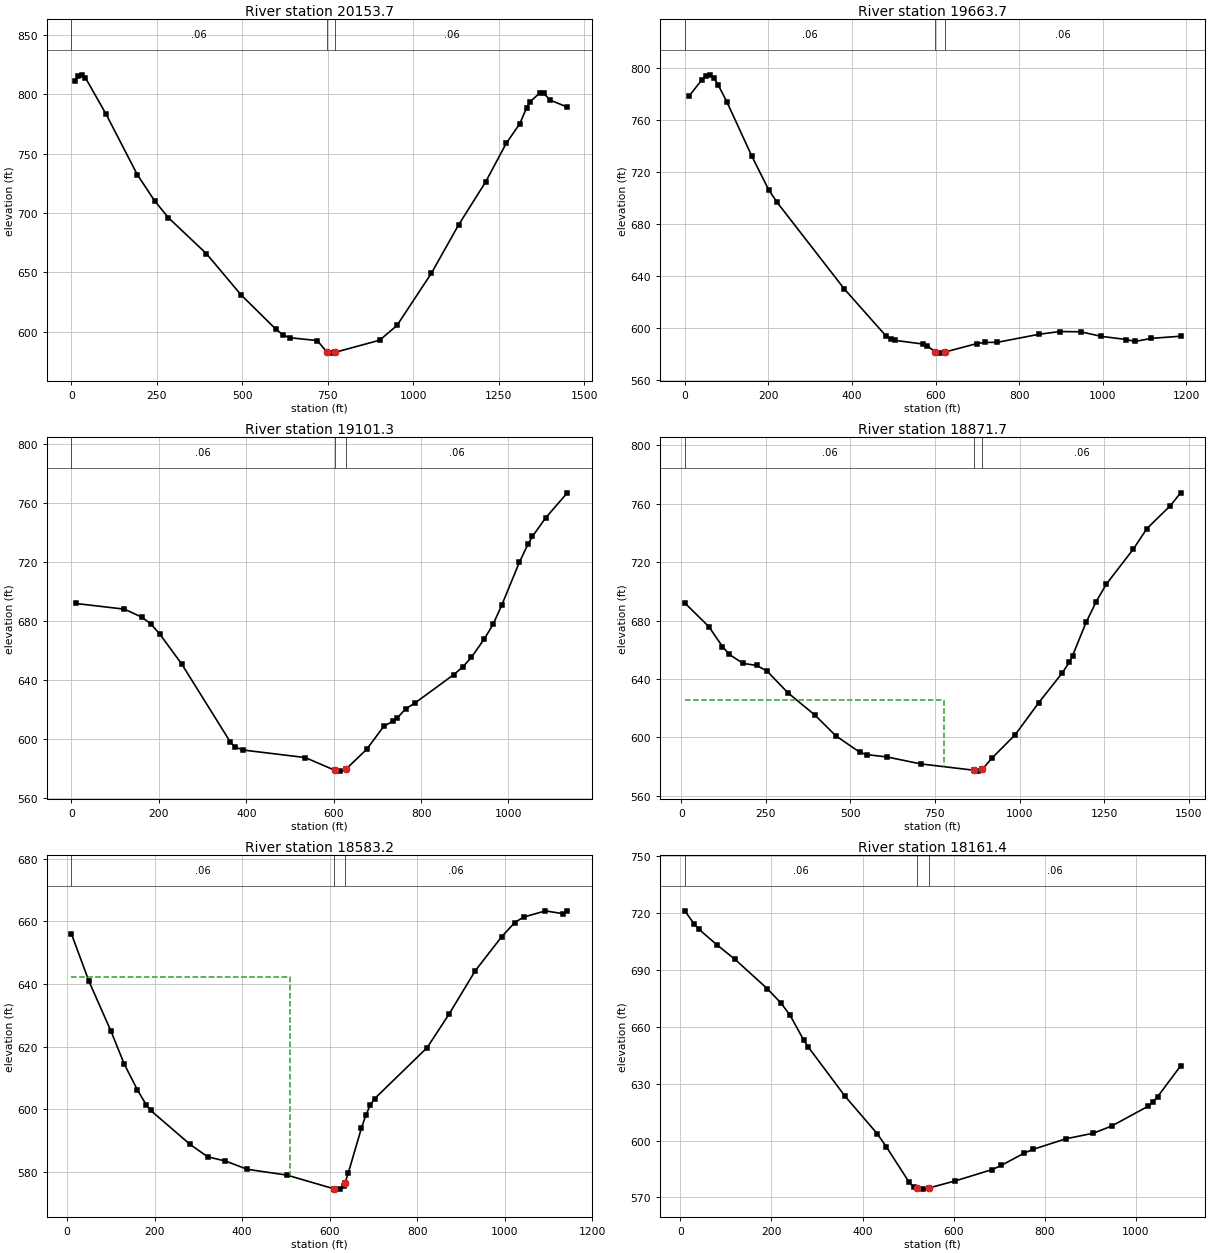
Type RM Length L Ch R = 1 ,20153.7 ,456.4,490,522.3
XS GIS Cut Line= 4
      1526424.57      450261.357     1527031.132      450299.267
       1527381.8      450095.501      1527800.44      450222.764
#Sta/Elev= 30
    10.1  811.47    20.3  814.99    30.4  816.38    40.5  814.08   101.3  783.27
   192.5  732.47   243.1  710.43   283.6  696.13     395  665.79   496.3  631.15
   597.6  602.42   617.9  597.69   638.2  595.14   719.3  592.67   747.3  583.09
   759.8  582.13   772.3  582.88   901.8  593.02   952.5  605.44  1053.1  649.33
  1132.7  690.06  1212.2  726.41  1271.9  758.63  1311.7  775.14  1331.5  788.49
  1341.5  793.63  1371.3  801.34  1381.3  800.86  1401.2  795.05  1450.9   789.2
#Mann= 3 , 0 , 0
       0     .06       0   747.3    .045       0   772.3     .06       0
Bank Sta=747.3,772.3
XS Rating Curve= 0 ,0
Exp/Cntr=0.3,0.1

Type RM Length L Ch R = 1 ,19663.7 ,563.9,562.5,561
XS GIS Cut Line= 4
     1526648.649      450530.253     1527140.123      450555.161
     1527334.413      450721.017     1527772.309      450743.711
#Sta/Elev= 30
      10  778.59    40.2   790.9    50.2  794.06    60.3  795.07    70.3  792.34
    80.3  787.06   100.4  774.48   160.7  732.26   200.9  706.49   220.9  696.86
   381.6  630.21   482.1  593.72   492.1  591.55   501.9  590.65   570.7  587.74
   580.5  586.38   597.5  581.99     610  580.79   622.5  581.64   698.4  588.13
   718.1  589.01   747.6  589.12   847.2  595.29     897  597.41   946.9  597.22
   996.7  593.68  1056.5  591.26  1076.4  589.76  1116.3  592.16    1186  593.81
#Mann= 3 , 0 , 0
       0     .06       0   597.5    .045       0   622.5     .06       0
Bank Sta=597.5,622.5
XS Rating Curve= 0 ,0
Exp/Cntr=0.3,0.1

Type RM Length L Ch R = 1 ,19101.3 ,231.6,229.6,227.6
XS GIS Cut Line= 3
     1526642.592      450697.637     1527100.091      451078.668
     1527519.663      451417.544
#Sta/Elev= 30
    10.1  691.91   121.1  688.06   161.5  682.54   181.6  678.02   201.8  671.24
   252.3  650.77   363.3  597.86   373.4  594.44   393.6  592.27   534.8  587.19
   602.9  578.51   615.4  577.96   627.9  579.26   675.3  592.67   715.2  608.63
   735.2  611.74   745.2  614.04   765.2  620.41   785.2  624.07     875   643.6
     895  648.65     915  655.21     945  667.96   964.9  677.78   984.9  690.96
  1024.9  719.87  1044.8  732.28  1054.8  737.46  1084.8  750.02  1134.7  767.13
#Mann= 3 , 0 , 0
       0     .06       0   602.9    .045       0   627.9     .06       0
Bank Sta=602.9,627.9
XS Rating Curve= 0 ,0
Exp/Cntr=0.3,0.1

Type RM Length L Ch R = 1 ,18871.7 ,295.7,288.5,279.3
XS GIS Cut Line= 4
     1526457.741      450550.422      1526700.32      451075.752
     1527106.952      451346.534     1527505.008       451441.31
#Sta/Elev= 30
    10.2  692.04    81.2  675.86   121.8  662.16   142.1  656.74   182.7  650.65
   223.3  649.23   253.8  645.33   314.7  630.63   395.9  615.08   456.8  601.09
   527.9  589.77   548.2  588.19   608.5  586.57   708.2  581.81   865.2  577.49
   877.7  576.88   890.2  578.15   917.6  585.57   987.4  601.83  1057.2  623.84
  1127.1  644.33    1147  651.37    1157  655.97  1196.9  678.74  1226.9  692.99
  1256.8  704.95  1336.6  728.91  1376.6  742.93  1446.4  758.71  1476.4  767.44
#Mann= 3 , 0 , 0
    10.2     .06       0   865.2    .045       0   890.2     .06       0
#XS Ineff= 2 , 0
          777.35  625.61
Permanent Ineff=
       F       F
Bank Sta=865.2,890.2
XS Rating Curve= 0 ,0
Exp/Cntr=0.3,0.1

Type RM Length L Ch R = 1 ,18583.2 ,412.6,421.8,429.6
XS GIS Cut Line= 3
     1526300.028      451277.643     1526862.554       451464.44
     1527382.161      451646.773
#Sta/Elev= 30
      10  656.01    50.2  640.83   100.5   624.9   130.6  614.47   160.7  606.22
   180.8  601.44   190.9  599.66   281.3  588.77   321.5  584.81   361.7  583.49
   411.9  580.83   502.3  578.99   610.3  574.59   622.8   574.5   632.8   575.5
   635.3  576.55   642.8  579.69   672.8  594.01   682.8   598.1   692.9  601.33
   702.9   603.4     823   619.7   873.1  630.41   933.1  644.29   993.2   655.1
  1023.3  659.67  1043.3  661.39  1093.3  663.38  1133.4  662.49  1143.4   663.4
#Mann= 3 , 0 , 0
      10     .06       0   610.3    .045       0   635.3     .06       0
#XS Ineff= 2 , 0
          508.63   642.2
Permanent Ineff=
       F       F
Bank Sta=610.3,635.3
XS Rating Curve= 0 ,0
Exp/Cntr=0.3,0.1

Type RM Length L Ch R = 1 ,18161.4 ,429.6,426.6,424.8
XS GIS Cut Line= 3
      1526192.37      451412.877     1526597.905      451742.476
     1527059.564      452085.782
#Sta/Elev= 30
      10  721.17    30.1  714.42    40.2  711.64    80.4  703.26   120.6  695.51
   190.9  680.13   221.1  672.53   241.2  666.03   271.3  652.83   281.4  649.18
   361.8  623.32   432.1  603.64   452.2  596.71   502.5  577.91   512.5  575.34
   520.2   574.8  532.57  574.36   545.2  574.94   603.3  578.69   684.1  584.65
   704.3  586.85   754.7  593.36   774.9  595.38   845.6  600.88   906.1  603.84
   946.5  607.62  1027.2  618.16  1037.3  620.35  1047.4  623.12  1097.9  639.36
#Mann= 3 , 0 , 0
      10     .06       0   520.2    .045       0   545.2     .06       0
Bank Sta=520.2,545.2
XS Rating Curve= 0 ,0
Exp/Cntr=0.3,0.1

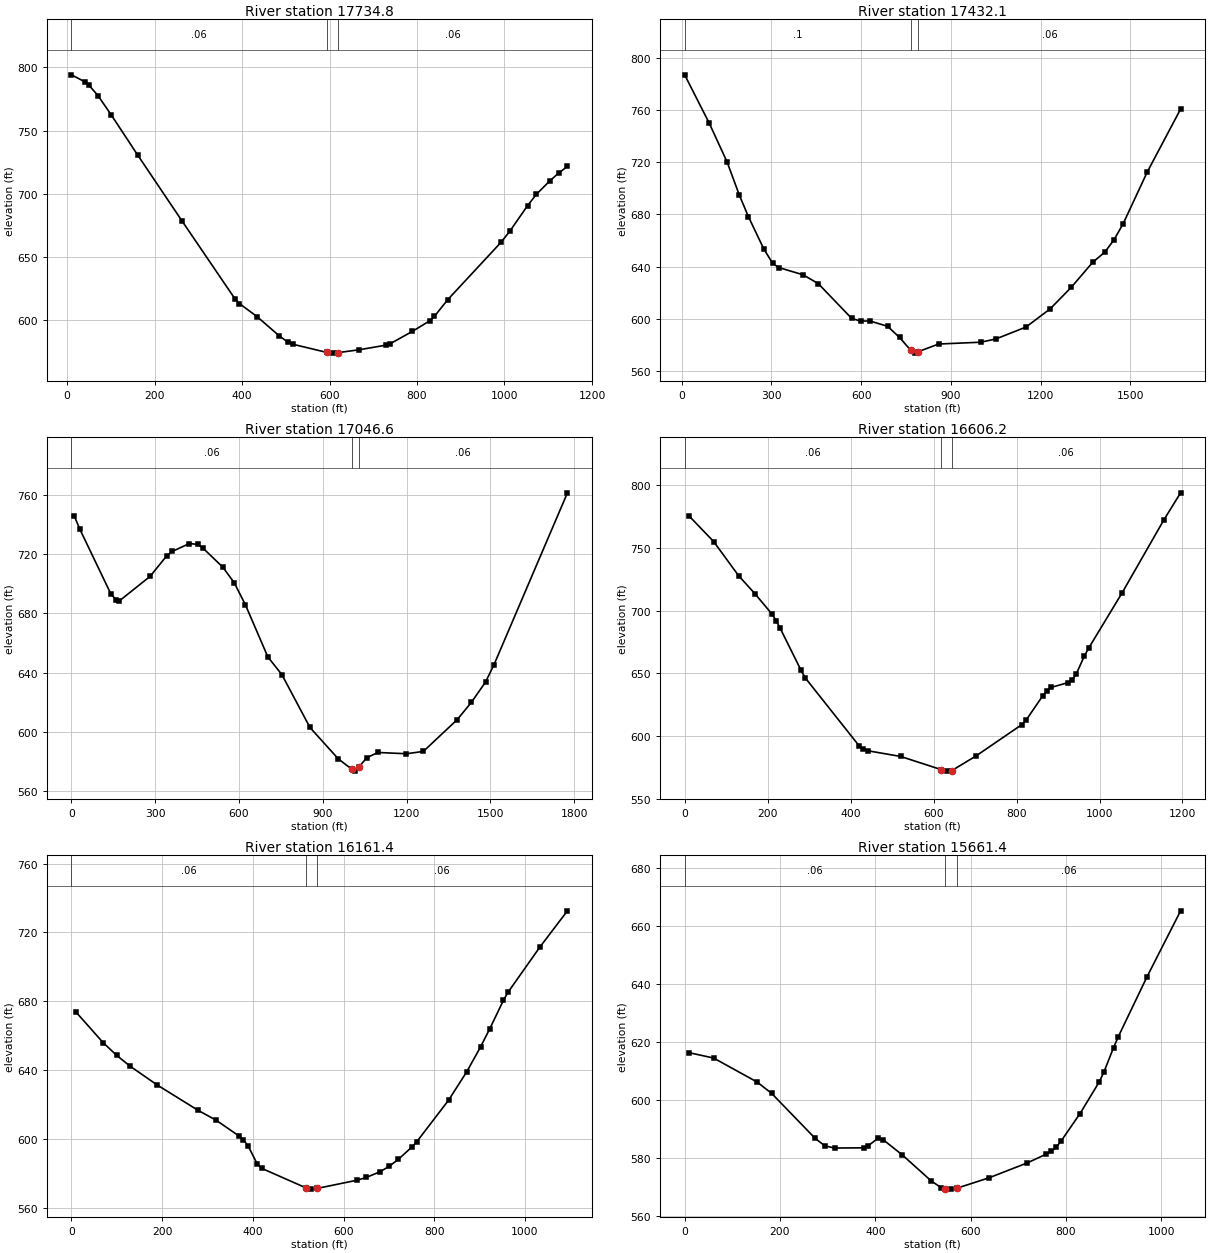
Type RM Length L Ch R = 1 ,17734.8 ,307.1,302.7,298.2
XS GIS Cut Line= 3
     1525976.117      451691.042     1526230.281      452005.223
     1526856.384      452399.207
#Sta/Elev= 30
    10.1  794.03    40.4  788.58    50.5  785.67    70.7  777.61     101  762.38
   161.6  730.57   262.7  678.65   383.9  617.04     394  613.32   434.5  602.98
   485.2  587.76   505.4  582.67   515.6  581.23   594.3  574.67  607.29  574.16
   619.3  574.55   667.6   576.8   728.4  580.42   738.5  581.54   789.2  591.29
   829.7  599.84   839.9  603.24   870.3  616.42   991.9  661.64  1012.1  670.43
  1052.7  690.64  1072.9  699.61  1103.3  710.14  1123.6  716.33  1143.9   721.7
#Mann= 3 , 0 , 0
    10.1     .06       0   594.3    .045       0   619.3     .06       0
Bank Sta=594.3,619.3
XS Rating Curve= 0 ,0
Exp/Cntr=0.3,0.1

Type RM Length L Ch R = 1 ,17432.1 ,409.4,385.5,361.7
XS GIS Cut Line= 4
     1525500.511      451853.582     1525950.693      452166.341
     1526377.182      452341.675     1526931.618      452697.082
#Sta/Elev= 30
    10.2   787.1    91.4  750.48   152.3  720.13   192.9  694.89   223.3  678.32
   274.1  653.82   304.5  642.44   324.8  639.27     406  633.72   456.8  626.96
   568.2  600.33   598.3  598.16   628.4  598.35   688.5  594.21   728.6  585.65
   766.2   575.7  778.97  573.64   791.2  574.78   858.9  580.62   999.3  582.01
  1049.8  584.45  1151.1  593.64  1232.2  607.66  1303.1  624.28    1374   643.3
  1414.6  651.12    1445  660.48  1475.4  672.69  1556.4  712.57  1667.9  760.87
#Mann= 3 , 0 , 0
    10.2      .1       0   766.2    .045       0   791.2     .06       0
Bank Sta=766.2,791.2
XS Rating Curve= 0 ,0
Exp/Cntr=0.3,0.1

Type RM Length L Ch R = 1 ,17046.6 ,415,440.4,465.8
XS GIS Cut Line= 4
     1525329.915      452270.593     1526088.118      452663.911
     1526396.137      452507.532     1526903.185       452782.38
#Sta/Elev= 30
      10  745.53    30.1  736.58   140.7  693.17   160.8  688.82   170.8   688.2
   281.4   704.8   341.7  718.79   361.8  721.73     422  726.94   452.2  726.41
   472.3  723.65   542.6  710.94   582.8  700.55     623  685.66   703.4  650.52
   753.7  638.55   854.1  602.97   955.7  581.79  1004.2  574.81  1016.7  573.53
  1029.2  576.12  1057.3  582.56    1098   586.1  1199.6  585.25  1260.3  586.82
  1381.7  608.28  1432.3  619.91  1482.9  633.56  1513.3  645.28  1776.3  761.16
#Mann= 3 , 0 , 0
       0     .06       0  1004.2    .045       0  1029.2     .06       0
Bank Sta=1004.2,1029.2
XS Rating Curve= 0 ,0
Exp/Cntr=0.3,0.1

Type RM Length L Ch R = 1 ,16606.2 ,445.9,444.8,443.2
XS GIS Cut Line= 3
     1525642.674      452697.082     1526201.848      452943.498
     1526727.845      453198.211
#Sta/Elev= 30
      10  775.83    70.1  755.11   130.2  727.85   170.3  713.22   210.4  697.31
   220.4  692.15   230.4  685.86   280.5  652.44   290.5  646.45   420.7  592.06
   430.7  589.34   440.8  588.23   520.9  583.61   618.7   573.1   631.2  571.92
   643.7   572.3   701.7   583.9   812.6  609.01   822.7  612.45     863     632
     873  636.15   883.1  638.72   923.4   642.5   933.5  644.36   943.6  649.22
   963.7  664.01   973.8  670.08  1054.4   714.2  1155.2  772.51  1195.5  794.07
#Mann= 3 , 0 , 0
       0     .06       0   618.7    .045       0   643.7     .06       0
Bank Sta=618.7,643.7
XS Rating Curve= 0 ,0
Exp/Cntr=0.3,0.1

Type RM Length L Ch R = 1 ,16161.4 ,510.9,500,489.9
XS GIS Cut Line= 3
     1525497.496      453082.581     1525983.261      453292.264
     1526505.129      453507.411
#Sta/Elev= 30
      10  673.71    69.9  655.92    99.8  648.52   129.8  642.17   189.7  631.24
   279.5  616.57   319.4  610.81   369.4  601.72   379.3  599.42   389.3  596.03
   409.3  585.64   419.3  582.94   516.6  571.62   529.1  570.84   541.6  571.24
   629.9  576.04     650  577.62   680.3  580.93   700.4  584.07   720.6  588.11
   750.8  595.35   760.9  598.21   831.5   622.5   871.8  639.12     902  653.47
   922.2  663.93   952.4   680.5   962.5  685.18  1033.1  711.57  1093.6  732.53
#Mann= 3 , 0 , 0
       0     .06       0   516.6    .045       0   541.6     .06       0
Bank Sta=516.6,541.6
XS Rating Curve= 0 ,0
Exp/Cntr=0.3,0.1

Type RM Length L Ch R = 1 ,15661.4 ,559.1,535.6,513.8
XS GIS Cut Line= 3
     1525475.237       453833.17      1526028.78      453762.078
     1526509.868      453725.394
#Sta/Elev= 30
    10.1  616.21    60.9  614.38   152.2  606.09   182.6  602.18     274  586.64
   294.3  584.08   314.6  583.33   375.4   583.4   385.6  584.17   405.9  586.73
     416  586.26   456.6  580.97   517.5  571.95   537.8  569.71   545.6  569.34
   558.1  569.15   570.6  569.43   638.5  573.05   718.9   578.2   759.1  581.27
   769.2  582.17   779.2  583.56   789.3  585.62   829.5  595.21   869.7   606.1
   879.7  609.57   899.8  617.94   909.9  621.78   970.2  642.46  1040.6  665.19
#Mann= 3 , 0 , 0
       0     .06       0   545.6    .045       0   570.6     .06       0
Bank Sta=545.6,570.6
XS Rating Curve= 0 ,0
Exp/Cntr=0.3,0.1