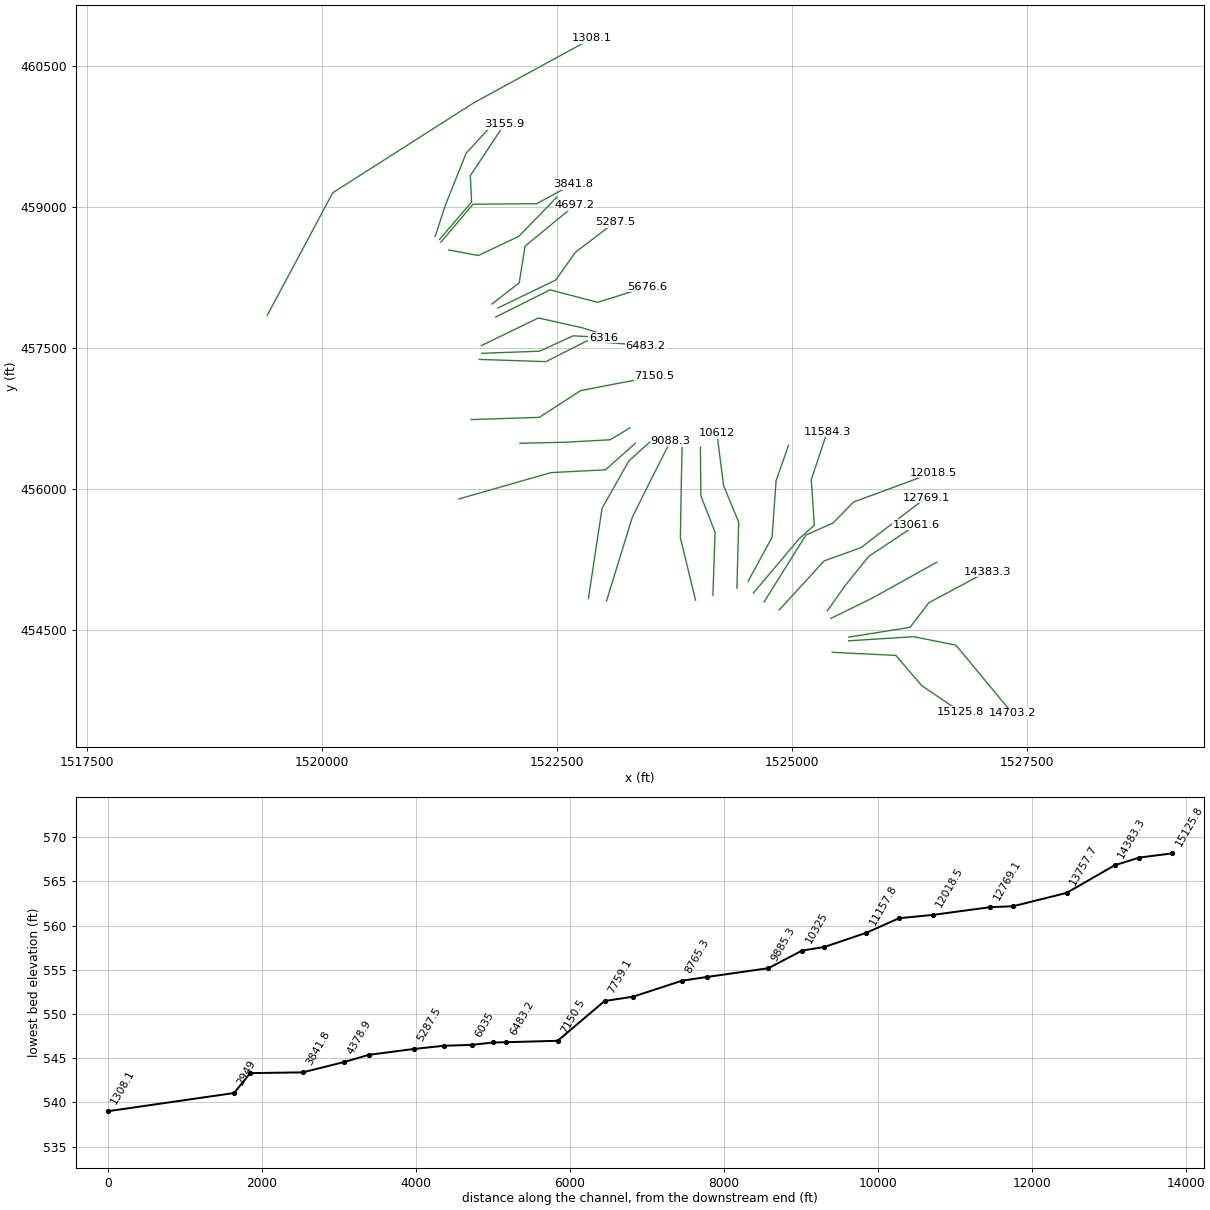
HEC-RAS study GRAGSTNCR.prj: GRAGSTNCR

--- GRAGSTNCR.g01 (geometry) --- (continued)

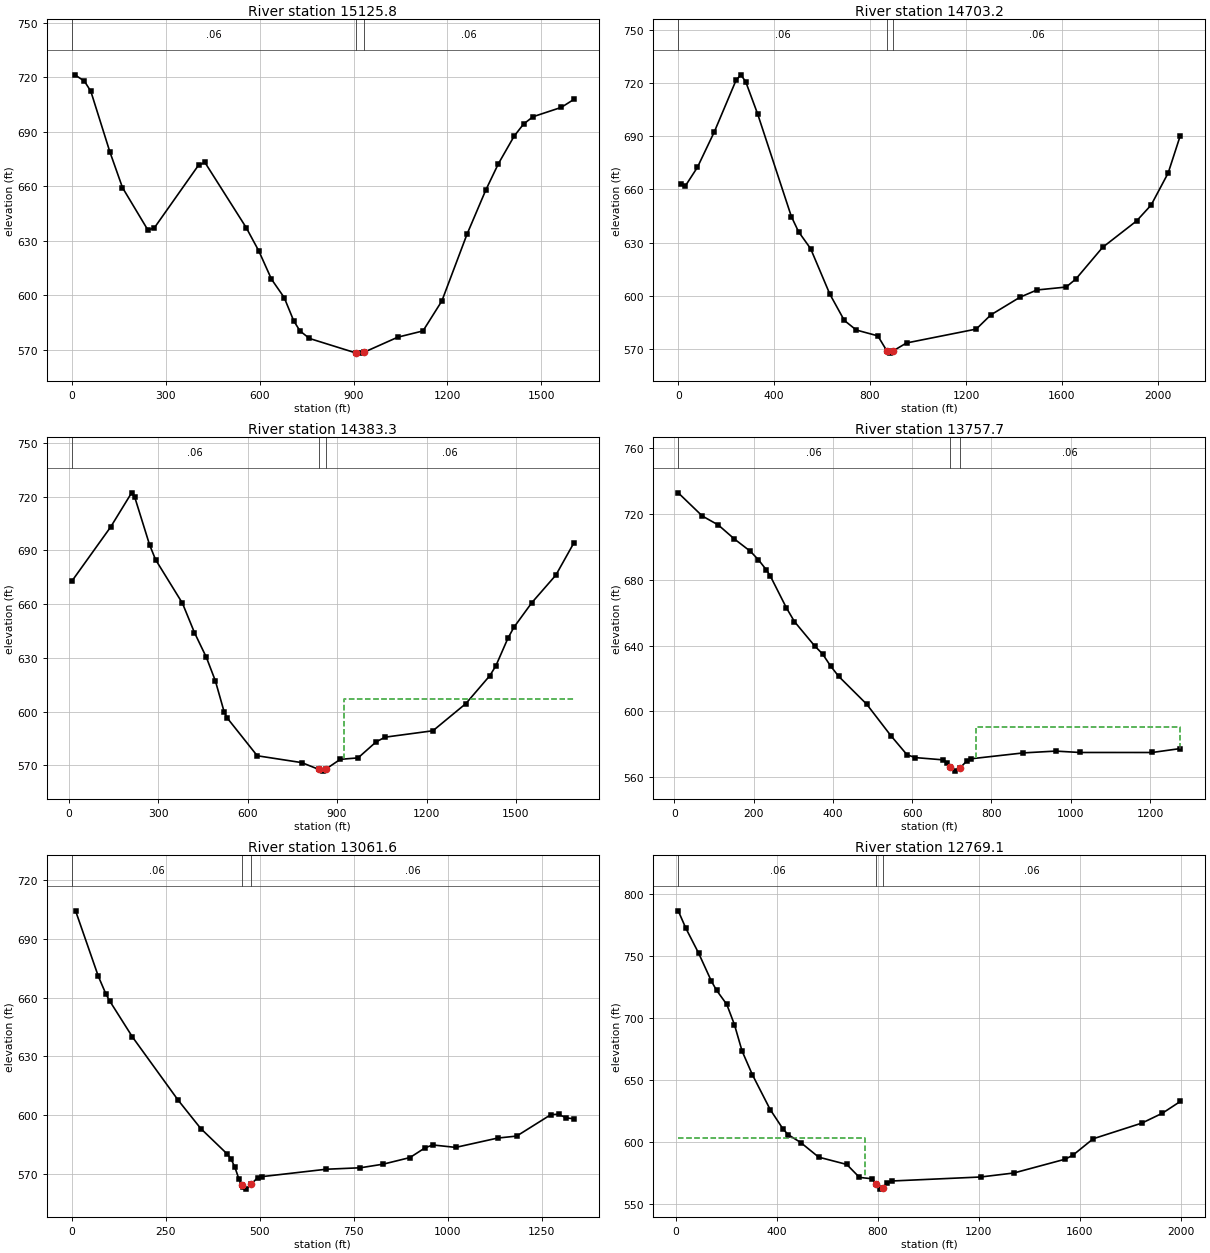
Type RM Length L Ch R = 1 ,15125.8 ,403.5,422.6,442
XS GIS Cut Line= 4
     1525429.429      454265.613     1526107.073      454232.442
     1526383.008      453911.501     1526798.932      453630.619
#Sta/Elev= 30
    10.1  721.41    40.5  717.89    60.8  712.37   121.5  679.07     162  659.29
     243  635.99   263.3  637.04     405  671.68   425.3  673.15   556.9  637.34
   597.4  624.43   637.9  608.86   678.5  598.76   708.7  586.02   728.8   580.4
   759.1  576.25   907.8  568.25   920.3  568.17   932.8   568.6  1041.2  576.95
  1121.8   580.4    1182  596.88  1262.3   633.6  1322.5  658.02  1362.7   672.5
  1412.9  687.64    1443  694.31  1473.1  698.33  1563.4  703.48  1603.6  707.86
#Mann= 3 , 0 , 0
       0     .06       0   907.8    .045       0   932.8     .06       0
Bank Sta=907.8,932.8
XS Rating Curve= 0 ,0
Exp/Cntr=0.3,0.1

Type RM Length L Ch R = 1 ,14703.2 ,288.9,319.9,351.4
XS GIS Cut Line= 4
     1525605.345      454387.904     1526296.623       454431.47
     1526746.806      454341.434     1527348.629      453616.403
#Sta/Elev= 30
      10  662.96    30.1  662.03    80.3  672.53   150.6  692.49   240.9  721.46
     261   724.6   281.1  720.82   331.3   702.5   471.8  644.71   501.9  636.12
   552.1  626.61   632.4  600.93   692.7  586.12   742.6  580.73   832.4  577.43
   869.8  569.03   882.3   567.7   894.8  568.85   952.1  573.43  1242.9  581.26
  1303.7  589.25  1425.3  599.22  1496.2  603.31  1617.8  604.95  1658.3  609.47
  1769.8  627.31  1911.6  642.22  1972.4   651.2  2043.4  669.27    2094  690.39
#Mann= 3 , 0 , 0
       0     .06       0   869.8    .045       0   894.8     .06       0
Bank Sta=869.8,894.8
XS Rating Curve= 0 ,0
Exp/Cntr=0.3,0.1

Type RM Length L Ch R = 1 ,14383.3 ,637.4,625.6,613.8
XS GIS Cut Line= 4
     1525604.764      454426.731     1526258.713      454530.984
     1526457.741      454791.616     1527078.519       455123.33
#Sta/Elev= 30
      10  672.78   140.5  703.08   210.7  722.13   220.7  719.98   270.9  693.15
     291  684.86   381.3  660.49   421.4  644.17   461.5   630.3   491.6  617.22
   521.7  599.55   531.8  596.39   632.1   575.4   781.5  571.58   838.5   567.8
     851  566.83   863.5  568.11   910.6  573.41   970.3  574.22  1030.4  583.09
  1060.5  585.77  1221.4  589.36    1332  604.54  1412.4  620.14  1432.6  625.64
  1472.8  640.95  1492.9  647.08  1553.2  660.86  1633.7  676.21    1694  694.15
#Mann= 3 , 0 , 0
      10     .06       0   838.5    .045       0   863.5     .06       0
#XS Ineff= 2 , 0
                          924.13          607.24
Permanent Ineff=
       F       F
Bank Sta=838.5,863.5
XS Rating Curve= 0 ,0
Exp/Cntr=0.3,0.1

Type RM Length L Ch R = 1 ,13757.7 ,686.8,696.1,705.4
XS GIS Cut Line= 3
     1525415.213      454625.759     1525851.179      454839.004
     1526543.039      455222.844
#Sta/Elev= 30
    10.1   732.9    70.8   718.8   111.2  713.34   151.7  704.84   192.1  697.34
   212.3  692.22   232.6     686   242.7  682.17   283.1  662.89   303.3  654.59
   353.9  639.91   374.1  634.97   394.3  627.64   414.5   621.4   485.3  604.43
   546.2  585.33   586.8  573.75     607  571.95   678.1  570.55   688.2   568.8
     696  566.25   708.5   563.7     721  565.65   738.9  570.15   749.1  571.22
   880.9  574.79   962.1  575.88  1022.9  575.04  1205.5  575.03  1276.5  577.42
#Mann= 3 , 0 , 0
    10.1     .06       0     696    .045       0     721     .06       0
#XS Ineff= 2 , 0
                          761.95          590.77
Permanent Ineff=
       F       F
Bank Sta=696,721
XS Rating Curve= 0 ,0
Exp/Cntr=0.3,0.1

Type RM Length L Ch R = 1 ,13061.6 ,307.6,292.5,277.5
XS GIS Cut Line= 4
     1525377.303      454706.318     1525576.331      454985.906
     1525818.008      455284.448     1526325.056        455620.9
#Sta/Elev= 30
    10.1  704.36    70.7  670.89    90.8  661.88   100.9  658.31   161.5   639.9
   282.6  607.73   343.2  593.14   413.9  580.07   424.1  577.45   434.2  573.26
   444.3  567.58     452  564.16   454.4   563.1   464.5  562.19     477  564.68
   494.8  568.09   504.9  568.55   676.8  572.35   767.9   573.1   828.7  574.95
   899.7  578.31   940.3  583.33   960.6  584.75  1021.4  583.51    1133  588.27
  1183.7  589.29    1275  600.27  1295.2  600.45  1315.5  598.57  1335.8  598.14
#Mann= 3 , 0 , 0
       0     .06       0     452    .045       0     477     .06       0
Bank Sta=452,477
XS Rating Curve= 0 ,0
Exp/Cntr=0.3,0.1

Type RM Length L Ch R = 1 ,12769.1 ,738.9,750.6,762.4
XS GIS Cut Line= 4
     1524865.516      454715.796     1525344.131       455237.06
     1525737.449      455379.223     1526429.309      455909.965
#Sta/Elev= 30
    10.1  786.23    40.4  772.14      91  752.06   141.5  729.53   161.8  722.24
   202.2   710.9   232.5  694.64   262.8  673.32   303.3  654.38   374.1  626.22
   424.6  610.63   444.8  606.04   495.4  599.55   566.1  587.85   677.3  581.97
   727.6  571.54   777.4  570.44   794.7   565.9  806.98  562.09   819.7  563.01
   837.1  567.14     857  568.65    1207  571.86  1338.8  575.08  1541.6  586.18
    1572  589.32  1653.1  602.66  1845.8  615.28  1926.9  623.23  1997.9  632.71
#Mann= 3 , 0 , 0
    10.1     .06       0   794.7    .045       0   819.7     .06       0
#XS Ineff= 2 , 0
           748.8  603.42
Permanent Ineff=
       F       F
Bank Sta=794.7,819.7
XS Rating Curve= 0 ,0
Exp/Cntr=0.3,0.1

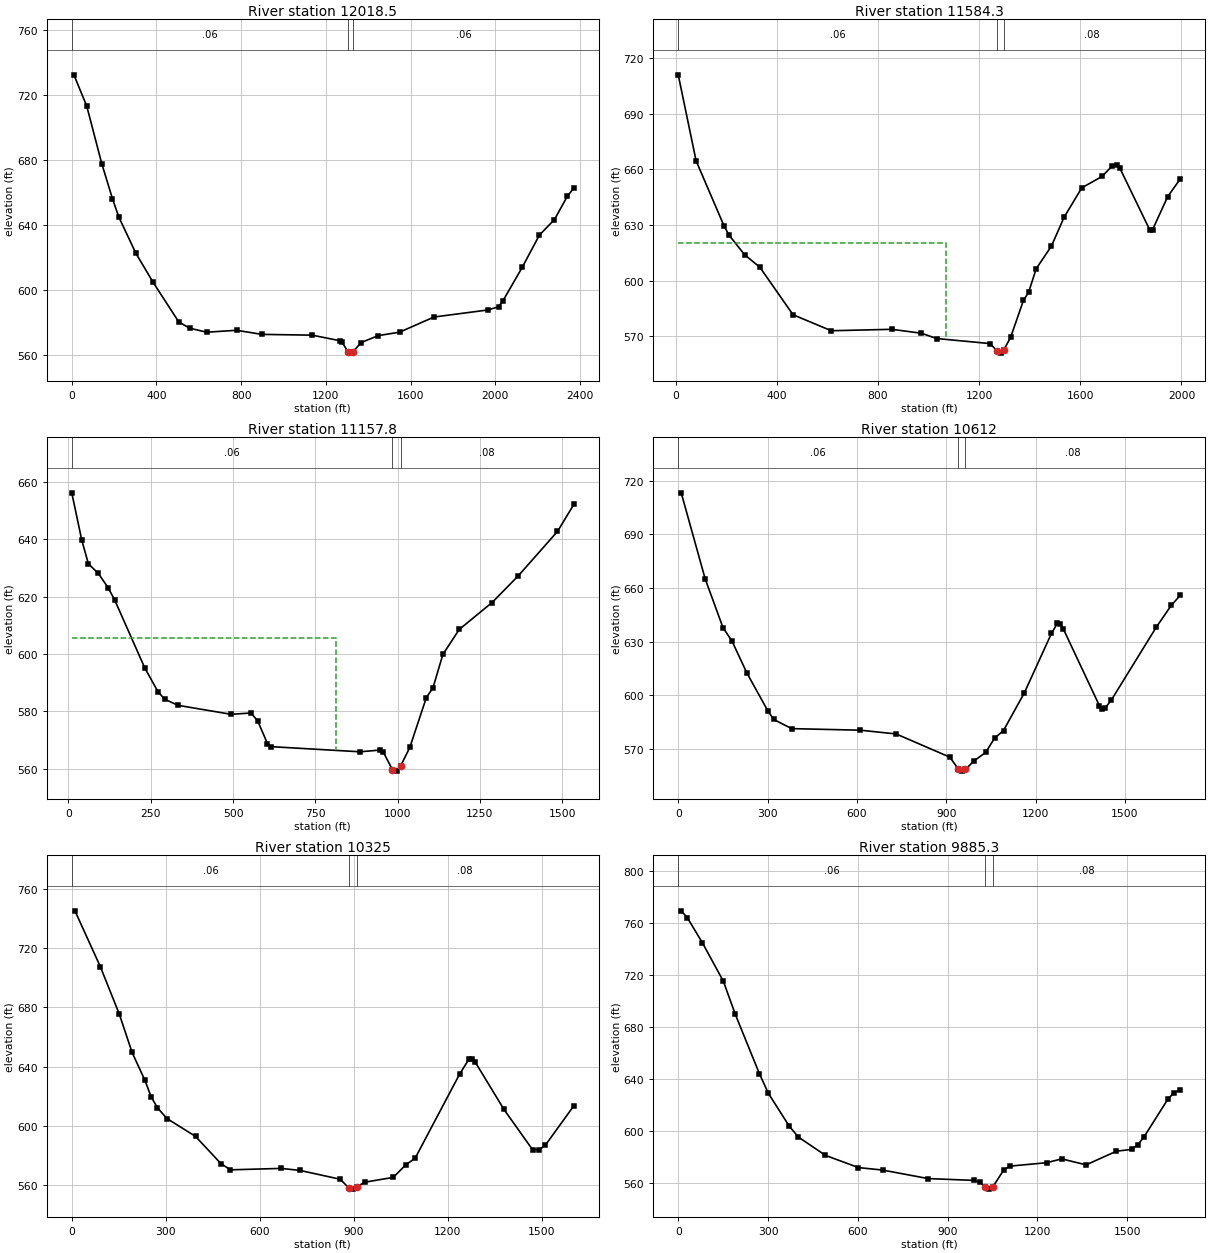
Type RM Length L Ch R = 1 ,12018.5 ,409.5,434.2,458.9
XS GIS Cut Line= 5
     1524704.398      454801.094     1525149.842      455511.908
     1525438.907      455639.855      1525656.89      455862.577
     1526505.129      456175.336
#Sta/Elev= 30
    10.1  732.53    70.7  713.27   141.5  677.92     192  656.31   222.3  644.94
   303.2  622.56   384.1  604.81   505.3   580.4   555.9   576.6   636.7  574.09
   778.2  575.27   898.1  572.75  1135.2  572.27  1265.6  568.86  1275.6  568.17
  1303.3  562.16  1315.8  561.21  1328.3  562.14  1366.1  567.69  1446.5  571.97
  1547.9  574.11  1710.4  583.44  1964.4  587.77  2015.1  589.75  2035.5  593.32
  2126.9  614.01  2208.1  633.89  2279.3  643.45  2340.2  657.83  2370.7  662.87
#Mann= 3 , 0 , 0
       0     .06       0  1303.3    .045       0  1328.3     .06       0
Bank Sta=1303.3,1328.3
XS Rating Curve= 0 ,0
Exp/Cntr=0.3,0.1

Type RM Length L Ch R = 1 ,11584.3 ,429.8,426.5,422.8
XS GIS Cut Line= 5
     1524590.668      454895.869     1525078.761      455473.998
     1525239.879      455616.161     1525206.707      456099.515
     1525377.303      456611.302
#Sta/Elev= 30
    10.1  711.04    80.7  664.65   191.7  629.34   211.9  624.38   272.4  613.96
   332.9  607.19   464.1  581.55   615.4  572.92   854.3  573.69   971.5  571.58
    1032  568.72    1244  565.98  1271.9  561.74  1284.4  560.84  1296.9  562.34
  1324.8  569.55  1375.2   589.3  1395.4  593.63  1425.7  606.43  1485.9  618.64
  1535.9  634.19  1605.8  650.06  1685.8  656.17  1725.7  661.83  1745.7  662.46
  1755.7  660.86  1875.6  627.06  1885.6  627.42  1945.5   645.3  1995.4  654.89
#Mann= 3 , 0 , 0
    10.1     .06       0  1271.9    .045       0  1296.9     .08       0
#XS Ineff= 2 , 0
         1068.53  620.37
Permanent Ineff=
       F       F
Bank Sta=1271.9,1296.9
XS Rating Curve= 0 ,0
Exp/Cntr=0.3,0.1

Type RM Length L Ch R = 1 ,11157.8 ,535.4,545.8,555.2
XS GIS Cut Line= 4
     1524533.803      455019.077     1524789.696      455488.215
     1524832.345      456090.038     1524964.987      456465.156
#Sta/Elev= 30
    10.1  656.22    40.3  639.82    60.5  631.49    90.7  628.14     121  623.06
   141.2  618.69   231.9  595.17   272.2  586.84   292.4  584.27   332.7  582.14
   494.1     579   554.5  579.46   574.6  576.78   604.8  568.78   614.8  567.73
   886.3  565.93   946.7  566.54   956.7  565.82   984.4  559.68   996.9  559.19
  1009.4  560.99  1037.2  567.46  1087.4  584.81  1107.6  588.25  1137.7  599.88
  1187.5   608.6  1286.9  617.95  1366.5  627.25  1485.9  642.76  1535.6  652.17
#Mann= 3 , 0 , 0
    10.1     .06       0   984.4    .045       0  1009.4     .08       0
#XS Ineff= 2 , 0
          812.18  605.49
Permanent Ineff=
       F       F
Bank Sta=984.4,1009.4
XS Rating Curve= 0 ,0
Exp/Cntr=0.3,0.1

Type RM Length L Ch R = 1 ,10612   ,286,287,289.5
XS GIS Cut Line= 4
     1524415.334      454947.996     1524434.289      455649.333
     1524273.171      456037.911     1524202.089      456597.086
#Sta/Elev= 30
      10  713.22    90.2  665.24   150.3   637.8   180.4  630.35   230.5  612.46
   300.7  591.34   320.7  586.47   380.9  581.35   611.4  580.47   731.6  578.38
   911.9   565.4   939.5  559.02     952  557.58   964.5  558.52     992  563.15
  1032.1     568  1062.2  575.99  1092.2   580.3  1162.5  601.47  1253.1  634.55
  1273.2  640.26  1283.3  639.84  1293.4     637  1414.2   594.2  1424.2  592.52
  1434.3  593.05  1454.4  597.35  1605.4  638.14  1655.7  650.31  1685.9  655.94
#Mann= 3 , 0 , 0
       0     .06       0   939.5    .045       0   964.5     .08       0
Bank Sta=939.5,964.5
XS Rating Curve= 0 ,0
Exp/Cntr=0.3,0.1

Type RM Length L Ch R = 1 ,10325   ,451,439.7,428
XS GIS Cut Line= 4
      1524159.44      454872.175     1524183.134      455540.341
     1524031.494       455928.92     1524026.755      456445.445
#Sta/Elev= 30
    10.1  745.32    91.2  707.55     152  675.33   192.5  649.59     233  630.94
   253.3  619.61   273.5  612.16   303.9   604.9   395.1   592.8   476.1  574.41
   506.5  570.23   668.6  571.19   728.2  569.83   857.3  563.84   884.5  557.83
     897  557.18   909.5  558.89   936.7  561.92  1026.1  565.13  1065.8  573.58
  1095.8  578.07  1237.6  634.86    1268  645.21  1278.1  645.31  1288.3  642.79
  1379.4  611.02  1470.6  583.83  1490.8  583.78  1511.1   586.8  1602.3  613.52
#Mann= 3 , 0 , 0
       0     .06       0   884.5    .045       0   909.5     .08       0
Bank Sta=884.5,909.5
XS Rating Curve= 0 ,0
Exp/Cntr=0.3,0.1

Type RM Length L Ch R = 1 ,9885.3  ,809.8,797,783.6
XS GIS Cut Line= 4
     1523974.628      454820.049     1523813.511      455483.476
     1523822.988      456052.128     1523832.466      456478.616
#Sta/Elev= 30
      10  769.48    30.1   764.3    80.3  745.05   150.6  715.38   190.8  689.73
   271.1  644.17   301.2  628.98   371.5  603.51   401.6  595.28     492  581.16
   602.4  571.76   682.7  569.88     835  563.31   987.4  561.91  1007.7  560.49
  1025.7  557.01  1038.2  555.18  1050.7  556.68  1088.9  570.29  1109.3  572.91
  1231.1  575.52  1281.9  578.47  1363.2  573.86  1464.7  584.42  1515.5  585.74
  1535.8  589.36  1556.2  595.21  1637.4   624.8  1657.7  629.54    1678  631.58
#Mann= 3 , 0 , 0
       0     .06       0  1025.7    .045       0  1050.7     .08       0
Bank Sta=1025.7,1050.7
XS Rating Curve= 0 ,0
Exp/Cntr=0.3,0.1

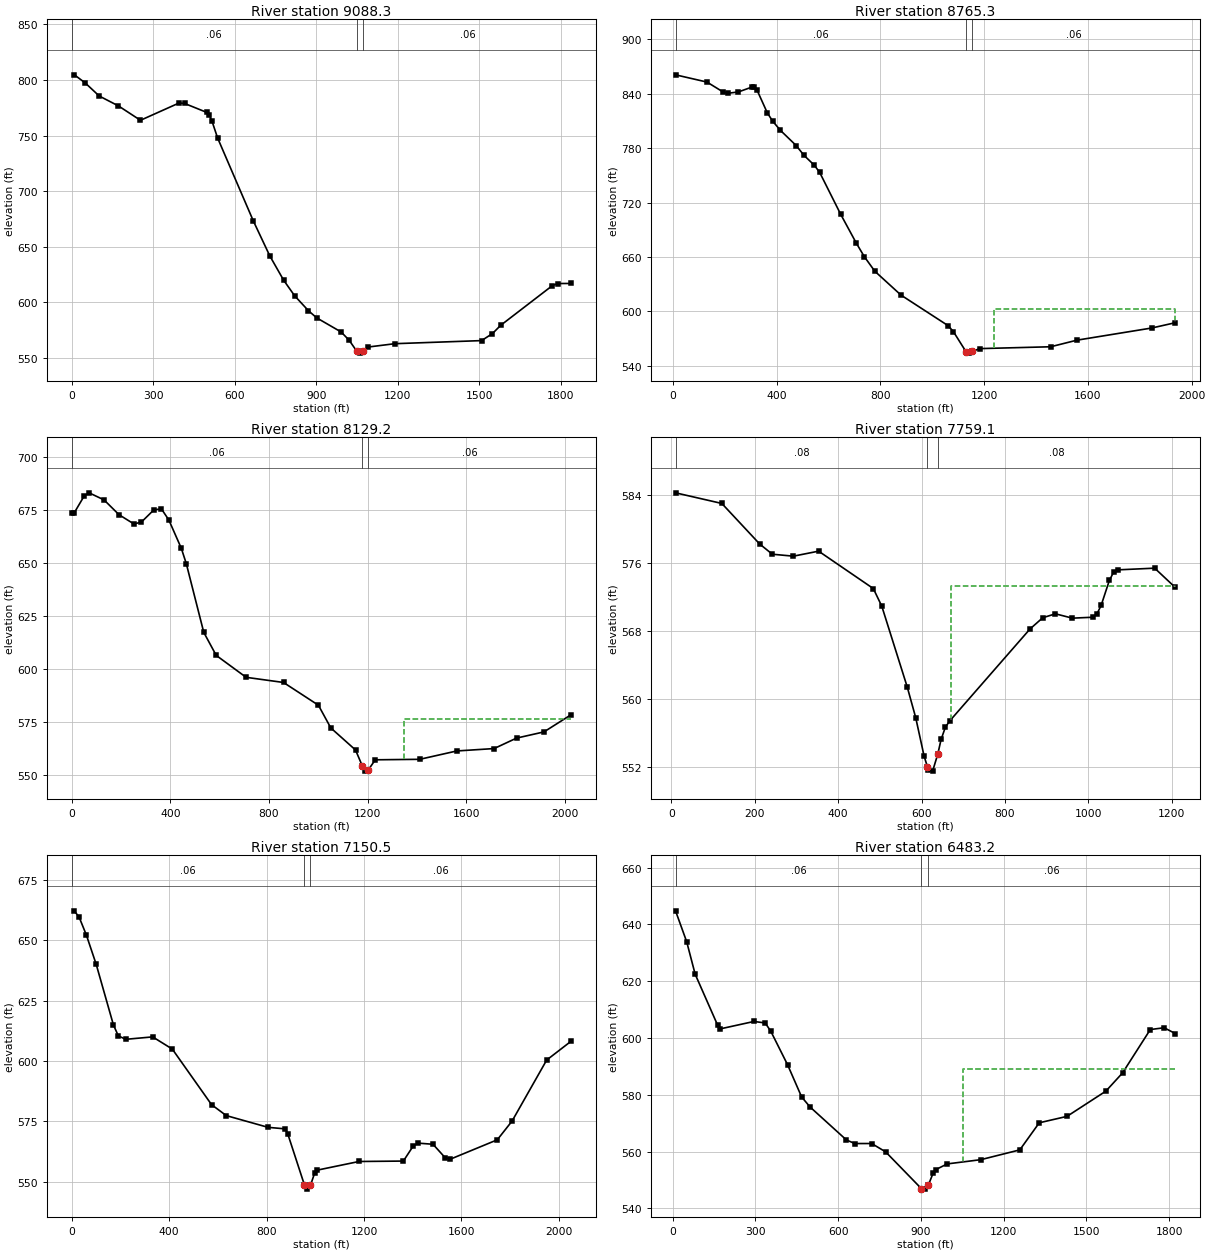
Type RM Length L Ch R = 1 ,9088.3  ,324.5,323,321.5
XS GIS Cut Line= 4
     1523026.876      454810.571     1523301.724      455701.459
     1523469.387      456038.449     1523709.258      456511.788
#Sta/Elev= 30
    10.1  804.69    50.7  797.23   101.3  785.65   172.3   776.7   253.3  763.77
   395.2  779.31   415.5  778.94   496.6  770.94   506.7  768.38   516.8  762.81
   537.1  747.93   668.8  673.11   729.6  641.59   780.3  619.84   820.8   605.8
   871.5  592.39   901.9  585.94   991.8  573.24  1021.5  565.77  1048.6  556.21
  1061.1  554.19  1073.6  555.99  1090.8  559.66  1189.9  562.69    1509  565.47
    1549  571.82    1579  579.18  1769.3  614.94  1789.3  616.84  1839.4   616.9
#Mann= 3 , 0 , 0
       0     .06       0  1048.6    .045       0  1073.6     .06       0
Bank Sta=1048.6,1073.6
XS Rating Curve= 0 ,0
Exp/Cntr=0.3,0.1

Type RM Length L Ch R = 1 ,8765.3  ,661.7,636.1,610.4
XS GIS Cut Line= 4
      1522834.47      454836.963     1522979.488      455796.234
     1523263.814      456298.543     1523552.878      456559.175
#Sta/Elev= 30
    10.1  860.91   131.4  852.91     192  842.23   212.2  840.55   252.6  842.05
   303.2  847.26   313.3  847.19   323.4   844.6   363.8     819     384  809.98
   414.3  799.66     475  782.91   505.3  772.04   545.7  760.98   565.9  753.13
   646.8  706.96   707.4  674.94   737.7  660.33   778.2   644.2   879.2  617.83
  1061.3  584.01  1081.6  577.34  1129.8  555.39  1142.3  553.77  1154.8  555.71
  1182.8  558.75  1456.2  560.79  1557.3  568.06  1846.8  581.54  1936.6  587.34
#Mann= 3 , 0 , 0
    10.1     .06       0  1129.8    .045       0  1154.8     .06       0
#XS Ineff= 2 , 0
                          1237.7          602.62
Permanent Ineff=
       F       F
Bank Sta=1129.8,1154.8
XS Rating Curve= 0 ,0
Exp/Cntr=0.3,0.1

Type RM Length L Ch R = 1 ,8129.2  ,372.4,370,367.8
XS GIS Cut Line= 4
      1521454.29      455895.067     1522435.809      456175.618
      1523016.21      456205.382     1523333.544      456487.349
#Sta/Elev= 30
       0  673.67    10.1  673.67    50.5  681.63    70.8  683.17   131.4  679.83
     192  672.86   252.7  668.48     283   669.4   333.5  675.15   363.9  675.62
   394.2  670.35   444.7  657.01   464.9  649.78   535.7  617.39   586.2  606.53
   707.5  596.19   859.1  593.76  1000.6  583.04  1050.9  572.33  1151.1  561.93
  1178.7  554.42  1191.2  551.96  1203.7  552.66  1231.2   557.3  1411.6  557.53
  1561.9  561.47  1713.2   562.6  1804.1  567.53  1915.3  570.45  2026.5  578.64
#Mann= 3 , 0 , 0
       0     .06       0  1178.7    .045       0  1203.7     .06       0
#XS Ineff= 2 , 0
                          1347.5          576.53
Permanent Ineff=
       F       F
Bank Sta=1178.7,1203.7
XS Rating Curve= 0 ,0
Exp/Cntr=0.3,0.1

Type RM Length L Ch R = 1 ,7759.1  ,594.5,608.7,622.8
XS GIS Cut Line= 4
     1522104.384      456487.397     1522588.683      456498.756
     1523065.324      456524.598     1523276.979      456651.297
#Sta/Elev= 30
    10.1   584.2   121.1  582.95   211.9  578.18   242.2  576.98   292.7  576.75
   353.2  577.34   484.4  572.94   504.7  570.87   565.7  561.37     586  557.77
   606.3  553.21   614.1  551.99   616.5  551.62   626.6  551.47   639.1  553.49
   646.9  555.19   657.1  556.62   667.2  557.35   860.2  568.19   890.7  569.51
   921.1  569.97   961.8  569.46  1011.1  569.57    1021  569.99  1030.8  570.97
  1050.6  573.92  1060.4  574.84  1070.3  575.14  1159.1  575.34  1208.5  573.07
#Mann= 3 , 0 , 0
    10.1     .08       0   614.1    .045       0   639.1     .08       0
#XS Ineff= 2 , 0
                           669.8          573.21
Permanent Ineff=
       F       F
Bank Sta=614.1,639.1
XS Rating Curve= 0 ,0
Exp/Cntr=0.3,0.1

Type RM Length L Ch R = 1 ,7150.5  ,661.4,667.2,663.5
XS GIS Cut Line= 4
     1521586.291      456739.248     1522311.322      456762.942
     1522752.027      457047.268     1523538.662      457198.909
#Sta/Elev= 30
    10.1  662.19    30.2   659.7    60.5  652.13   100.8  640.02   171.3     615
   191.4  610.45   221.7  608.99   332.5     610   413.1  604.95   574.3  581.93
   634.7  577.41   806.1  572.55   876.7  571.92   886.8   569.9     955  548.82
   967.5  546.97     980  548.48   997.7  553.76  1007.8  554.83  1179.3  558.41
  1361.4  558.59    1402  564.84  1422.3  566.01  1483.1  565.54  1533.8  559.88
  1554.1  559.37  1746.8  567.39  1807.6  575.15  1949.6  600.41    2051   608.3
#Mann= 3 , 0 , 0
       0     .06       0     955    .045       0     980     .06       0
Bank Sta=955,980
XS Rating Curve= 0 ,0
Exp/Cntr=0.3,0.1

Type RM Length L Ch R = 1 ,6483.2  ,177.6,167.2,161.9
XS GIS Cut Line= 4
     1521671.589      457378.982     1522382.404      457355.288
      1522817.03      457575.032     1523439.148      457525.883
#Sta/Elev= 30
    10.2  644.81    50.8  633.87    81.3  622.51   162.6  604.59   172.7  603.25
   294.6  605.85   335.3  605.33   355.6  602.41   416.6  590.58   467.4  579.28
   497.8  575.75   629.9  564.12   660.4  562.86   721.4  562.87   772.1  559.93
   901.6     547   914.1  546.81   926.6  548.14   944.6  552.54   954.7  553.72
   995.3  555.69  1117.1  557.18  1258.6  560.63  1329.1  570.17  1429.7  572.43
  1570.6  581.31    1631  587.71  1731.7     603    1782  603.64  1822.3  601.59
#Mann= 3 , 0 , 0
    10.2     .06       0   901.6    .045       0   926.6     .06       0
#XS Ineff= 2 , 0
                          1053.3          589.23
Permanent Ineff=
       F       F
Bank Sta=901.6,926.6
XS Rating Curve= 0 ,0
Exp/Cntr=0.3,0.1

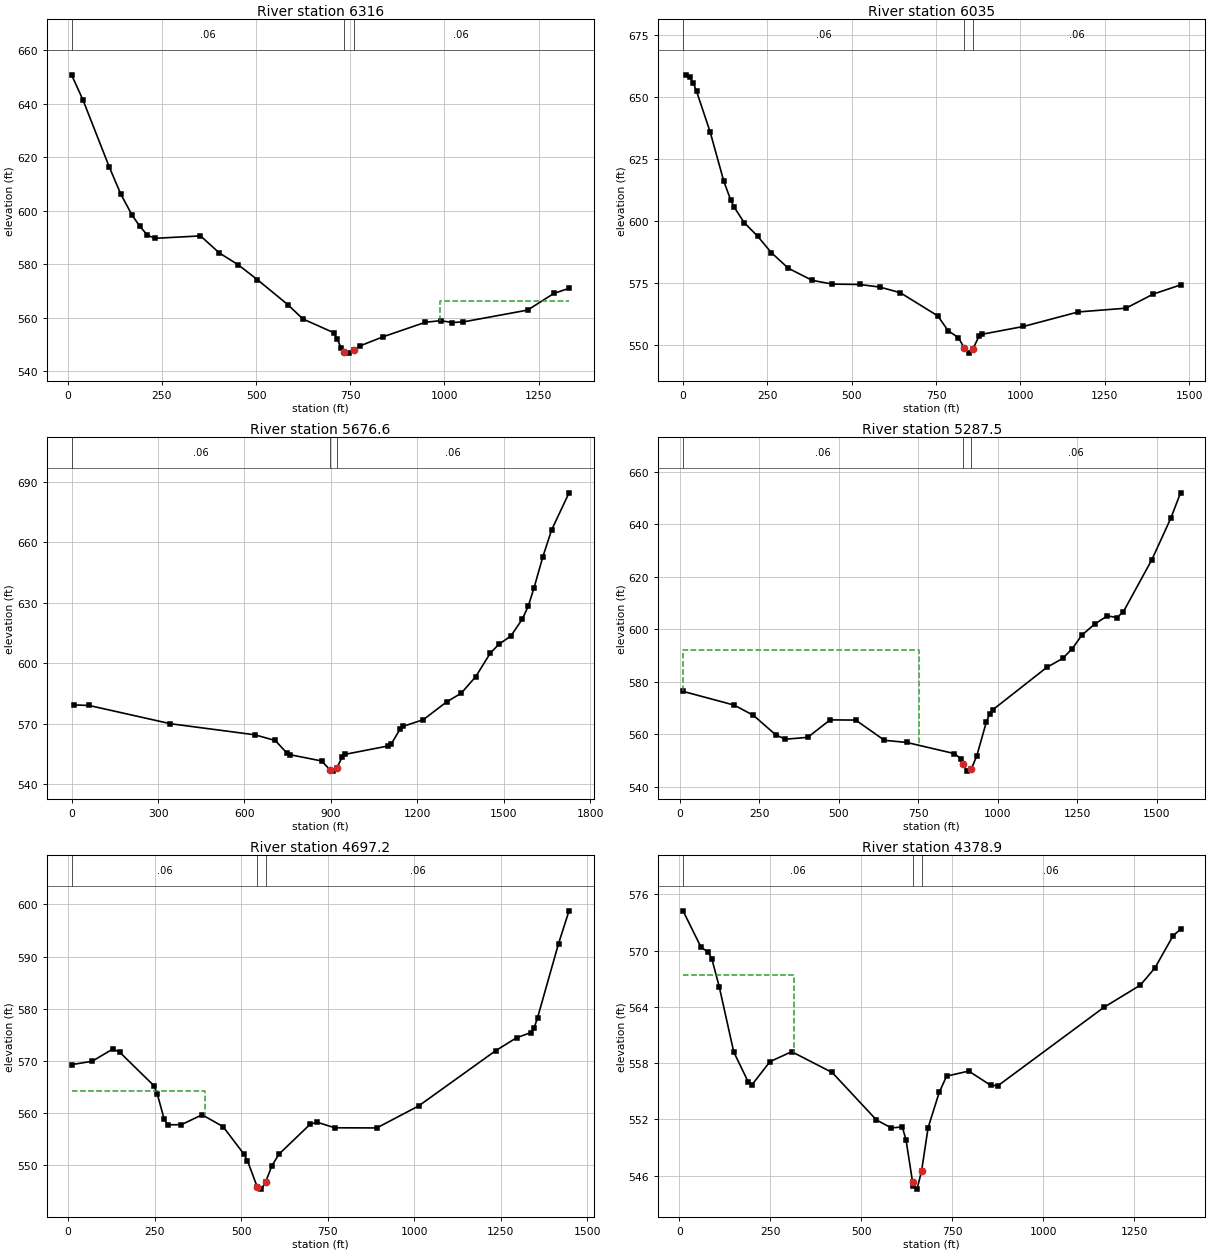
Type RM Length L Ch R = 1 ,6316    ,298.8,281.1,267.4
XS GIS Cut Line= 4
      1521699.48      457443.767     1522313.365       457466.09
     1522674.255      457629.793      1522994.22       457611.19
#Sta/Elev= 30
    10.1  650.87    40.3  641.52   110.8  616.22     141  606.21   171.2   598.3
   191.3  594.24   211.5  590.92   231.6  589.72   352.5  590.62   402.8  584.22
   453.2  579.77   503.5  574.26   584.1  564.95   624.5  559.55   705.7  554.46
   715.9  551.99   726.1  548.62   733.9  547.33  736.43  546.78   746.4  546.84
   758.9  547.92   776.9  549.53   837.8  552.92   949.6  558.32   990.3  558.92
  1020.6  558.23  1050.6  558.46  1220.9  562.87    1291  569.12  1331.1  571.01
#Mann= 3 , 0 , 0
    10.1     .06       0   733.9    .045       0   758.9     .06       0
#XS Ineff= 2 , 0
                           989.7          566.18
Permanent Ineff=
       F       F
Bank Sta=733.9,758.9
XS Rating Curve= 0 ,0
Exp/Cntr=0.3,0.1

Type RM Length L Ch R = 1 ,6035    ,359.7,358.4,357.4
XS GIS Cut Line= 4
     1521695.283      457525.883     1522301.845      457819.687
     1522767.268      457715.365     1523075.728      457618.386
#Sta/Elev= 30
    10.1  659.09    20.1  658.04    30.2  655.85    40.2  652.37    80.5  635.91
   120.7   616.1   140.8  608.62   150.9   605.7   181.1  599.32   221.3  593.77
   261.5  587.18   311.8  580.87   382.3  575.97   442.6  574.43   523.1  574.28
   583.4  573.23   643.8  570.95   755.2  561.55   785.6  555.55     816  552.79
     834  548.44   846.5  546.51     859  548.24   876.9  553.26   887.1  554.16
  1008.9   557.3  1171.2  563.17  1312.6  564.69  1393.5   570.4  1474.3  574.09
#Mann= 3 , 0 , 0
       0     .06       0     834    .045       0     859     .06       0
Bank Sta=834,859
XS Rating Curve= 0 ,0
Exp/Cntr=0.3,0.1

Type RM Length L Ch R = 1 ,5676.6  ,355.2,389.1,422.8
XS GIS Cut Line= 4
     1521846.923      457829.164     1522425.053      458118.229
       1522932.1      457985.544     1523462.842        458151.4
#Sta/Elev= 30
    10.1  579.25    60.6  578.99   343.4  569.93   636.3  564.43   706.8  561.61
   747.2   555.4   757.2  554.59   868.1  551.44   895.9  547.21   908.4  546.41
   920.9  548.08   938.7  553.22   948.7  554.73  1099.9  558.93    1110  559.94
  1140.3  567.35  1150.3  568.61    1221  571.95  1301.9  580.78  1352.5  585.08
    1403  593.36  1453.6  605.04  1483.9  609.44  1524.3  613.39  1564.8  621.95
    1585  628.27  1605.2  637.46  1635.6  652.75  1665.9  666.05  1726.5  684.49
#Mann= 3 , 0 , 0
       0     .06       0   895.9    .045       0   920.9     .06       0
Bank Sta=895.9,920.9
XS Rating Curve= 0 ,0
Exp/Cntr=0.3,0.1

Type RM Length L Ch R = 1 ,5287.5  ,577.3,590.2,603
XS GIS Cut Line= 4
     1521870.775       457925.61     1522486.657      458222.482
     1522695.162      458516.285     1523116.912      458838.521
#Sta/Elev= 30
    10.1   576.4   170.9  571.18   231.3  567.29   301.6  559.87   331.8  558.19
   402.2   558.9   472.6  565.55     553  565.48   643.5  557.78   713.7  556.96
   863.8  552.71   883.8  550.77   891.4  548.64   903.9  546.05   916.4  546.82
   933.9  551.85   963.9  564.72   973.9  567.74   983.9  569.36  1154.1  585.54
  1204.2  588.94  1234.2  592.67  1264.3  597.78  1304.3  601.97  1344.4  605.14
  1374.4  604.49  1394.5  606.61  1484.6  626.54  1544.7  642.47  1574.7  651.96
#Mann= 3 , 0 , 0
    10.1     .06       0   891.4    .045       0   916.4     .06       0
#XS Ineff= 2 , 0
          751.27  592.31
Permanent Ineff=
       F       F
Bank Sta=891.4,916.4
XS Rating Curve= 0 ,0
Exp/Cntr=0.3,0.1

Type RM Length L Ch R = 1 ,4697.2  ,346,318.3,290.8
XS GIS Cut Line= 4
     1521808.962      457968.243     1522098.078      458194.049
     1522159.682      458582.628     1522690.423      459018.594
#Sta/Elev= 30
     9.9  569.27    69.4  569.91   128.9  572.26   148.7  571.68   247.9  565.22
   257.8  563.59   277.6  558.78   287.5  557.72   327.2  557.75     387  559.64
   447.6  557.38   508.1  552.08   518.2  550.82     546  545.85   558.5  545.38
     571  546.83   588.8  549.87     609  552.08   699.8  557.87   719.9  558.21
   770.4  557.15   891.6  557.12  1012.8  561.35    1235  571.94  1295.6  574.43
    1336   575.4  1346.1   576.3  1356.2  578.29  1416.8   592.5  1447.1  598.78
#Mann= 3 , 0 , 0
     9.9     .06       0     546    .045       0     571     .06       0
#XS Ineff= 2 , 0
          394.37  564.12
Permanent Ineff=
       F       F
Bank Sta=546,571
XS Rating Curve= 0 ,0
Exp/Cntr=0.3,0.1

Type RM Length L Ch R = 1 ,4378.9  ,549.4,537.1,524.8
XS GIS Cut Line= 4
     1521348.994      458542.062     1521662.111      458483.114
     1522093.339      458686.881     1522499.405      459104.412
#Sta/Elev= 30
      10  574.23    59.7  570.33    79.7  569.83    89.6  569.05   109.5  566.15
   149.4  559.19   189.2     556   199.1  555.67   248.9  558.15   308.7  559.22
   420.1     557   541.9  551.94   582.5   551.1   612.9  551.19   623.1  549.83
     641  545.36   643.3  544.87   653.5  544.57     666  546.53   683.9  551.12
   714.4  554.88   734.7  556.61   795.6  557.15   855.8  555.64   875.9  555.59
  1167.1  563.94  1267.5  566.31  1307.7  568.15  1357.9   571.6    1378  572.25
#Mann= 3 , 0 , 0
      10     .06       0     641    .045       0     666     .06       0
#XS Ineff= 2 , 0
          316.24  567.44
Permanent Ineff=
       F       F
Bank Sta=641,666
XS Rating Curve= 0 ,0
Exp/Cntr=0.3,0.1

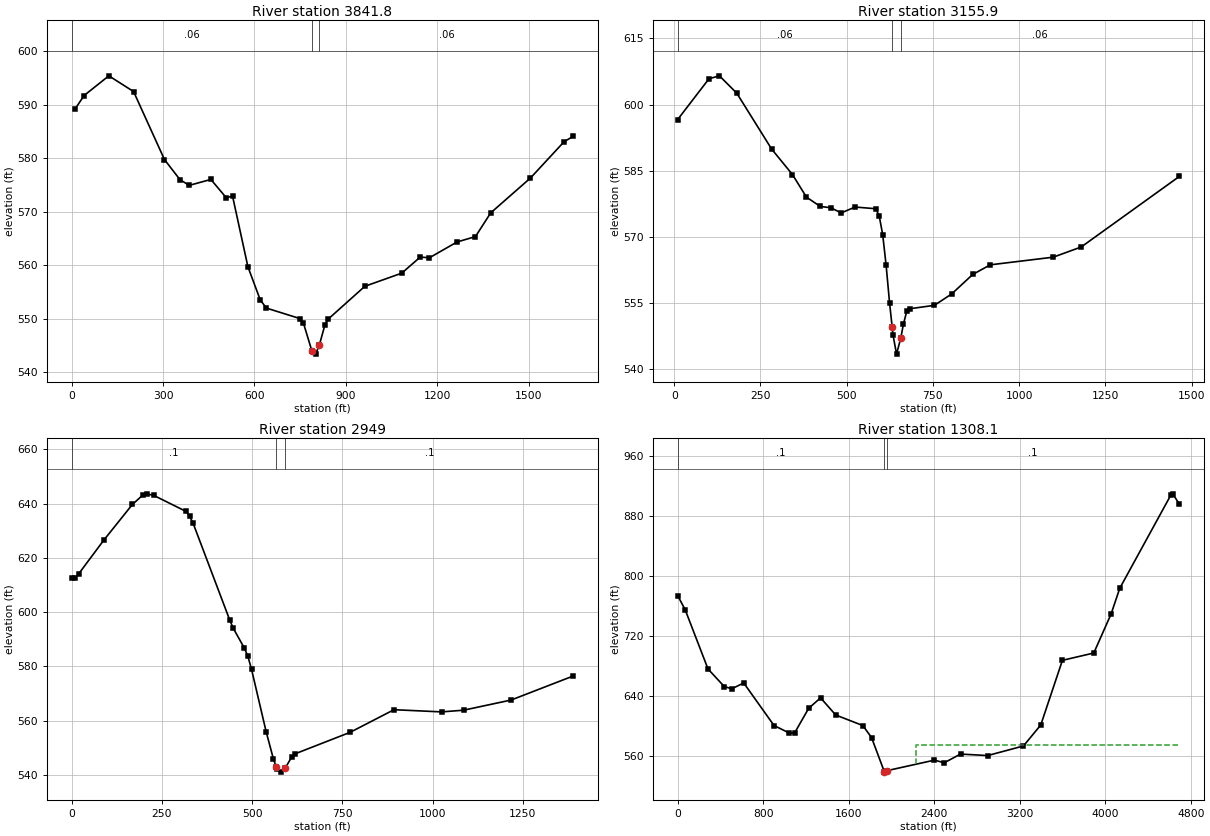
Type RM Length L Ch R = 1 ,3841.8  ,640.4,685.9,731.3
XS GIS Cut Line= 4
     1521264.055      458625.277     1521605.246      459028.072
     1522282.206      459034.172     1522671.697      459243.451
#Sta/Elev= 30
    10.2  589.17    40.6  591.75   121.8  595.43     203  592.49   304.5  579.77
   355.3  576.02   385.8  574.95   456.8  576.06   507.6  572.62   527.9  572.97
   578.4  559.74   618.8  553.56     639  552.01   750.2  550.03   760.3  549.29
   788.2  544.05   800.7   543.4   813.2  545.14     831   548.8   841.1   549.9
   962.4  556.08  1083.6  558.54  1144.2  561.54  1174.6  561.42  1265.2  564.37
  1325.5  565.37  1375.7  569.81  1506.3  576.33  1616.9  583.13    1647  584.13
#Mann= 3 , 0 , 0
       0     .06       0   788.2    .045       0   813.2     .06       0
Bank Sta=788.2,813.2
XS Rating Curve= 0 ,0
Exp/Cntr=0.3,0.1

Type RM Length L Ch R = 1 ,3155.9  ,218.8,207,195.4
XS GIS Cut Line= 4
     1521249.443      458653.814      1521591.03      459051.766
     1521576.814      459331.353     1521941.699      459881.049
#Sta/Elev= 30
    10.1   596.6   100.9  605.86   131.1  606.52   181.5  602.57   282.4  589.89
   342.9  584.09   383.3  578.97   423.6  576.85   453.9  576.56   484.1  575.38
   524.4  576.72   584.4  576.33   594.4  574.66   604.4  570.45   614.4  563.45
   624.4  554.88   631.9  549.45   634.4  547.64  644.48  543.31   656.9  546.98
   664.4  550.09   674.4  553.12   684.4  553.63   754.4   554.4   804.4  556.98
   865.3   561.4   916.1  563.59  1098.8  565.33    1180  567.65  1464.2  583.66
#Mann= 3 , 0 , 0
    10.1     .06       0   631.9    .045       0   656.9     .06       0
Bank Sta=631.9,656.9
XS Rating Curve= 0 ,0
Exp/Cntr=0.3,0.1

Type RM Length L Ch R = 1 ,2949    ,1659.2,1640.9,1613.6
XS GIS Cut Line= 4
     1521202.749      458685.778     1521310.163       459014.95
     1521531.922      459569.346     1521833.374      459898.519
#Sta/Elev= 30
       0  612.79     9.9  612.79    19.8  614.25      89  626.59   168.2  639.74
   197.9   643.3   207.8  643.63   227.5  643.03   316.6  637.15   326.5  635.41
   336.4  632.73   437.3  597.25   447.5  594.08   477.8  586.87   487.9  583.79
   498.1  578.97   538.5  556.01   558.8  545.87   566.5  543.05   568.9  542.17
     579  541.06   591.5  542.56   609.4  546.65   619.5  547.85   771.3  555.73
   892.8  564.07  1024.5  563.26  1085.4  563.88  1217.3  567.63  1389.7  576.51
#Mann= 3 , 0 , 0
       0      .1       0   566.5    .045       0   591.5      .1       0
Bank Sta=566.5,591.5
XS Rating Curve= 0 ,0
Exp/Cntr=0.3,0.1

Type RM Length L Ch R = 1 ,1308.1  ,1326.3,1308.1,1289.9
XS GIS Cut Line= 4
     1519414.725      457846.979     1520112.436      459150.057
     1521610.462       460104.28     1522872.498       460791.73
#Sta/Elev= 30
       0  773.93    70.9  754.81   283.5  676.29   435.3  652.95   506.2  649.88
   617.6   657.7     901  601.02  1042.8  591.11  1093.4   591.1    1225  623.92
  1336.4  637.85  1478.1  615.03  1731.8  600.98    1813  585.06  1932.5  539.66
    1945     539  1957.5  540.95  2401.7  554.98    2493  551.44  2645.3  563.03
    2899  561.05  3233.9  573.82  3395.9  601.76  3598.3  687.77  3891.8  697.53
  4053.8  749.54  4134.7  783.67  4610.4  907.19  4630.6  909.37  4691.4  895.75
#Mann= 3 , 0 , 0
       0      .1       0  1932.5    .045       0  1957.5      .1       0
#XS Ineff= 2 , 0
                         2231.94          575.43
Permanent Ineff=
       F       F
Bank Sta=1932.5,1957.5
XS Rating Curve= 0 ,0
Exp/Cntr=0.3,0.1
Stream Node=GRAGSTNCR       ,Main            , 0 , 0 ,Upstream end
Stream Node=GRAGSTNCR       ,Main            , 0 , 1 ,Downstream end

Chan Stop Cuts=-1
Use User Specified Reach Order=0